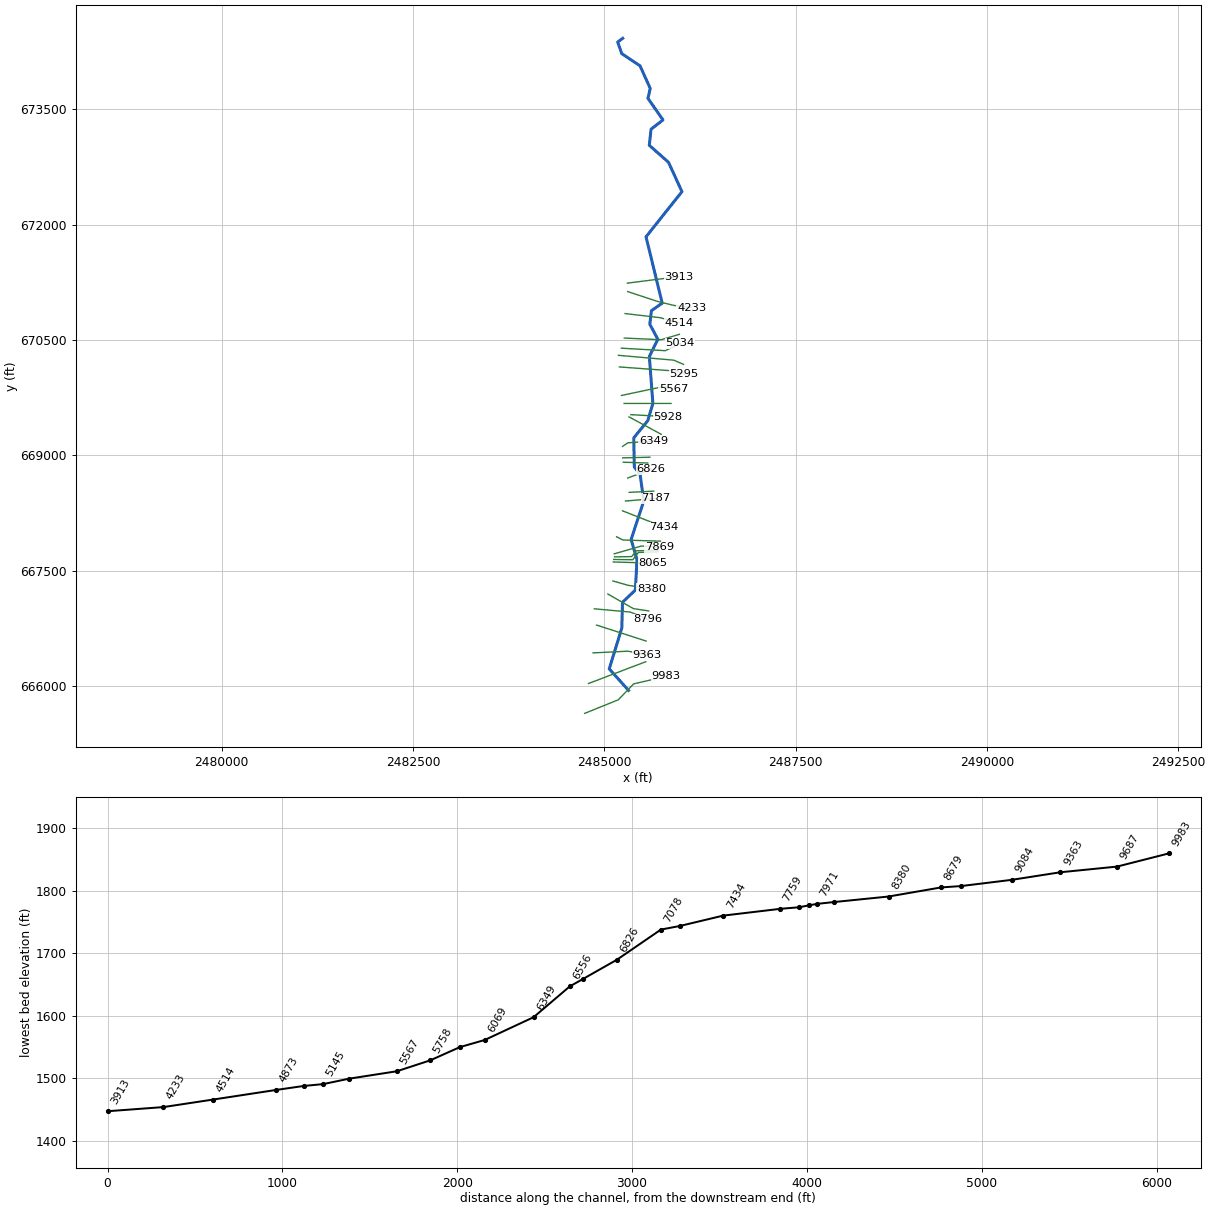
--- KESSNERRN.prj (project) ---

Proj Title=KESSNERRN
Current Plan=p01
Default Exp/Contr=0,0
English Units
Geom File=g01
Flow File=f01
Plan File=p01
BEGIN DESCRIPTION:
Stream Name: Kessner Run
Flood Zone: Approximate
Pendleton County, West Virginia
HEC-RAS Version: 5.0.7
Hydrology Method:
Regression equation
Model Notes:
END DESCRIPTION:
DSS Export Rating Curves= 0
DSS Export Rating Curve Sorted= 0
DSS Export Volume Flow Curves= 0
DXF OffsetX= 0
DXF OffsetY= 0
DXF ScaleX= 0
DXF ScaleY= 0

--- KESSNERRN.p01 (plan) ---

Plan Title=Floodplain
Program Version=5.07
Short Identifier=Floodplain
Geom File=g01
Flow File=f01
Subcritical Flow
K Sum by GR= 0
Std Step Tol= 0.01
Critical Tol= 0.01
Num of Std Step Trials= 20
Max Error Tol= 0.3
Flow Tol Ratio= 0.001
Split Flow NTrial= 30
Split Flow Tol= 0.02
Split Flow Ratio= 0.02
Log Output Level= 0
Friction Slope Method= 1
Unsteady Friction Slope Method= 2
Unsteady Bridges Friction Slope Method= 1
Parabolic Critical Depth
Global Vel Dist= 0 , 0 , 0
Global Log Level= 0
CheckData=False
Encroach Param=-1 ,0,0, 0
Mapping Interval=1HOUR
Computation Time Step Use Courant=        0
Computation Time Step Use Time Series=    0
Computation Time Step Count To Double=0
Computation Time Step Max Doubling=0
Computation Time Step Max Halving=0
Computation Time Step Residence Courant=0
Run HTab= 0
Run UNet= 0
Run Sediment= 0
Run PostProcess= 0
Run WQNet= 0
Run RASMapper= 0
UNET Theta= 0
UNET Theta Warmup= 0
UNET ZTol= 0
UNET ZSATol= 0
UNET MxIter= 0
UNET Max Iter WO Improvement= 0
UNET MaxInSteps= 0
UNET DtIC= 0
UNET DtMin= 0
UNET MaxCRTS= 0
UNET WFStab= 0
UNET SFStab= 0
UNET WFX= 1
UNET SFX= 1
UNET 1D Methodology=Finite Difference
UNET DSS MLevel= 1
UNET Pardiso=0
UNET DZMax Abort= 0
UNET Use Existing IB Tables= 0
UNET Froude Reduction=False
UNET Froude Limit= 0
UNET Froude Power= 0
UNET D1 Cores= 0
UNET D2 Coriolis=0
UNET D2 Cores= 0
UNET D2 Theta= 1
UNET D2 Theta Warmup= 1
UNET D2 Z Tol= 0.01
UNET D2 Volume Tol= 0.01
UNET D2 Max Iterations= 20
UNET D2 Equation= 0
UNET D2 RampUpFraction=0.1
UNET D2 TimeSlices= 1
UNET D2 BCVolumeCheck=0
UNET D1D2 MaxIter= 0
UNET D1D2 ZTol=0.01
UNET D1D2 QTol=0.1
UNET D1D2 MinQTol=1
Write IC File= 0
Write IC File at Fixed DateTime=0
Write IC File at Sim End=0
Echo Input=False
Echo Parameters=False
Echo Output=False
Write Detailed= 0
HDF Write Warmup=0
HDF Write Time Slices=0
HDF Flush=0
HDF Face Node Velocities=0
HDF Compression= 1
HDF Chunk Size= 1
HDF Spatial Parts= 1
HDF Use Max Rows=0
HDF Fixed Rows= 1
Calibration Method= 0
Calibration Iterations= 20
Calibration Max Change=0.05
Calibration Tolerance=0.2
Calibration Maximum=1.5
Calibration Minimum=0.5
Calibration Optimization Method= 1
WQ AD Non Conservative
WQ ULTIMATE=-1
WQ Max Comp Step=1HOUR
WQ Output Interval=15MIN
WQ Output Selected Increments= 0
WQ Output face flow=0
WQ Output face velocity=0
WQ Output face area=0
WQ Output face dispersion=0
WQ Output cell volume=0
WQ Output cell surface area=0
WQ Output cell continuity=0
WQ Output cumulative cell continuity=0
WQ Output face conc=0
WQ Output face dconc_dx=0
WQ Output face courant=0
WQ Output face peclet=0
WQ Output face adv mass=0
WQ Output face disp mass=0
WQ Output cell mass=0
WQ Output cell source sink temp=0
WQ Output nsm pathways=0
WQ Output nsm derived pathways=0
WQ Output MaxMinRange=-1
WQ Daily Max Min Mean=-1
WQ Daily Range=0
WQ Daily Time=0
WQ Create Restart=0
WQ Fixed Restart=0
WQ System Summary=0
WQ Write To DSS=0
WQ Use Fixed Temperature=0
Sorting and Armoring Iterations= 10
XS Update Threshold= 0.02
Bed Roughness Predictor= 0
Hydraulics Update Threshold= 0.02
Energy Slope Method= 1
Volume Change Method= 1
Sediment Retention Method= 0
XS Weighting Method= 0
Number of US Weighted Cross Sections= 1
Number of DS Weighted Cross Sections= 1
Upstream XS Weight=0
Main XS Weight=1
Downstream XS Weight=0
Number of DS XS's Weighted with US Boundary= 1
Upstream Boundary Weight= 1
Weight of XSs Associated with US Boundary= 0
Number of US XS's Weighted with DS Boundary= 1
Downstream Boundary Weight= 0.5
Weight of XSs Associated with DS Boundary= 0.5
Percentile Method= 0
Sediment Output Level= 3
Mass or Volume Output= 0
Output Increment Type= 1
Profile and TS Output Increment= 1
XS Output Flag= 0
XS Output Increment= 10
Write Gradation File= 0
Read Gradation Hotstart= 0
Write HDF5 File= 1
Write Binary Output= 1
Write DSS Sediment File= 0
SV Curve= 0
Specific Gage Flag= 0

--- KESSNERRN.f01 (steady flow) ---

Flow Title=Flows
Program Version=5.07
Number of Profiles= 6
Profile Names=P100yr,P10yr,P25yr,P50yr,P500yr,P101yr
River Rch & RM=KESSNERRN,Main            ,9983
     491     230     325     406     719     598
River Rch & RM=KESSNERRN,Main            ,9363
     624     292     412     515     916     760
River Rch & RM=KESSNERRN,Main            ,6069
     709     331     468     585    1042     863
River Rch & RM=KESSNERRN,Main            ,4514
     791     368     521     652    1163     962
River Rch & RM=KESSNERRN,Main            ,0
     792     369     522     653    1164     963
Boundary for River Rch & Prof#=KESSNERRN,Main            , 1
Up Type= 0
Dn Type= 1
Dn Known WS=1348.6
Boundary for River Rch & Prof#=KESSNERRN,Main            , 2
Up Type= 0
Dn Type= 1
Dn Known WS=1347.55
Boundary for River Rch & Prof#=KESSNERRN,Main            , 3
Up Type= 0
Dn Type= 1
Dn Known WS=1348.05
Boundary for River Rch & Prof#=KESSNERRN,Main            , 4
Up Type= 0
Dn Type= 1
Dn Known WS=1348.33
Boundary for River Rch & Prof#=KESSNERRN,Main            , 5
Up Type= 0
Dn Type= 1
Dn Known WS=1349.4
Boundary for River Rch & Prof#=KESSNERRN,Main            , 6
Up Type= 0
Dn Type= 1
Dn Known WS=1349.02
DSS Import GetInterval= 0
DSS Import GetPeak= 0
DSS Import FillOption= 0

--- KESSNERRN.g01 (geometry) ---

Geom Title=Geometry
Program Version=5.07

River Reach=KESSNERRN       ,Main
Reach XY= 30
2485317.31299999665941.7910000092485064.89800003666221.800000012
2485229.43300003666753.275000021     2485238.296667088.378999993
      2485406.56667247.9310000092485427.74200001667644.443000004
2485350.96100003667904.2660000182485515.73900002668406.408000022
2485467.99161491668754.8673125512485392.48200002668848.606000006
     2485385.484669227.1099999992485568.24400002669450.518999994
2485635.26900002      669674.5662485589.08700001670285.678000018
2485700.49200001670509.219999999     2485594.836670705.898000002
2485616.03799999670881.3070000112485757.07900003      670980.059
2485545.54800001671843.1630000172486014.94400001672430.260000005
2485839.94700003672811.9080000222485588.27599999673033.780000001
2485611.08027226673242.0745860192485767.07910535673363.895800605
2485570.51300001 673644.767000022485600.67700002673773.153000012
2485467.60299999674067.2840000092485228.54500002674226.301000014
2485174.99800003      674377.4342485240.98468331674425.178490251

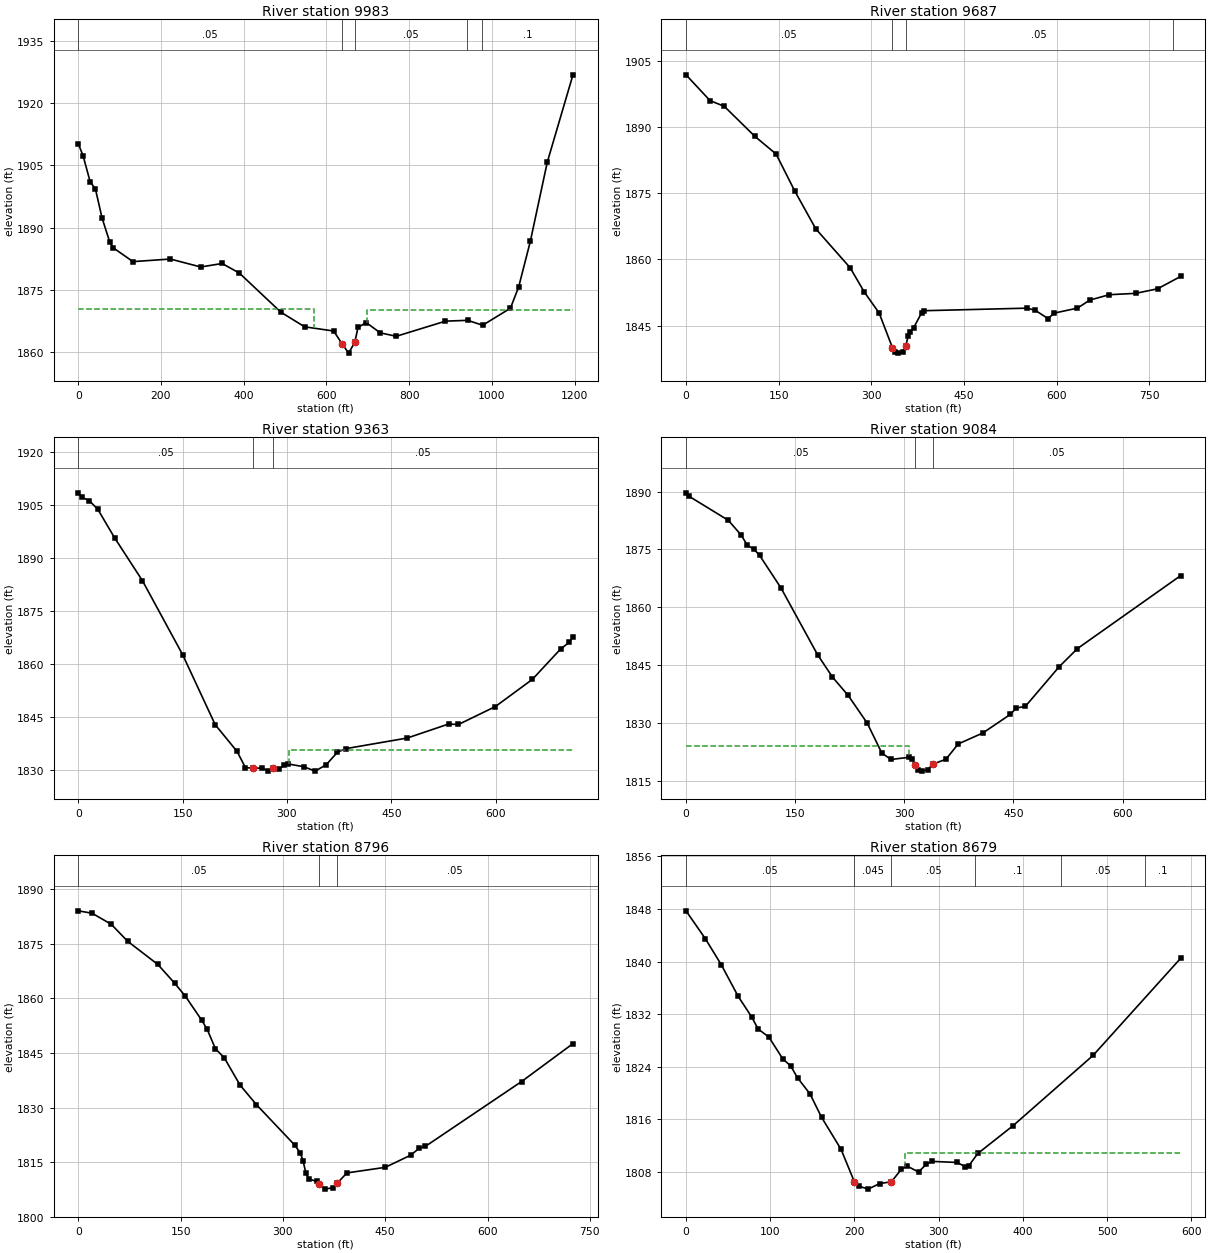
Type RM Length L Ch R = 1 ,9983    ,302.4,295.8,288.6
XS GIS Cut Line= 4
 2484744.1133678665642.8143950822485183.59463255665819.662021023
2485383.97749668666026.6691120682485807.21226123666123.664688645
#Sta/Elev= 30
       0 1910.18    11.5 1907.31    28.7 1901.05    41.6 1899.24    57.4 1892.35
    76.1 1886.53    84.8 1885.12   132.2 1881.82   222.7 1882.44     296 1880.53
   347.8 1881.37   389.5 1879.06   489.8 1869.66   547.3 1866.14   617.4 1865.13
   638.11862.012   653.6 1859.81   668.51862.422   676.3 1865.98   696.1 1867.16
     730 1864.69   768.8 1863.86   887.7  1867.5   941.3  1867.7   977.7 1866.52
  1044.8 1870.61  1064.8 1875.75    1093 1886.73    1134 1905.78    1196 1926.75
#Mann= 5 ,-1 , 0
       0     .05       0   638.1    .045       0   668.5     .05       0
  938.83      .1       0  976.76      .1       0
#XS Ineff= 2 , 0
          569.74 1870.47  697.83         1870.15
Permanent Ineff=
       F       F
Bank Sta=638.1,668.5
XS Rating Curve= 0 ,0
Exp/Cntr=0.3,0.1

Type RM Length L Ch R = 1 ,9687    ,327.3,324,320.3
XS GIS Cut Line= 2
     2484794.412666031.2885985722485542.93690356666315.112096444
#Sta/Elev= 30
       0 1901.92    38.9 1896.07      62 1894.76   111.6 1887.93   145.8 1883.94
   175.7 1875.62     210 1866.96   265.6 1858.13   288.4 1852.64   312.6 1847.83
     334 1839.99     338 1838.89   342.6 1838.74   351.1 1838.96   355.4 1840.35
   359.7 1842.66   362.9  1843.6   368.3 1844.48   381.1 1847.84   385.4 1848.37
   552.1 1848.95     565 1848.47   586.2 1846.56     595  1847.8   633.5 1848.96
   653.2 1850.77   684.8    1852   727.6 1852.31     763 1853.34   800.5 1856.15
#Mann= 4 ,-1 , 0
       0     .05       0     334    .045       0   355.4     .05       0
  787.88      .1       0
Bank Sta=334,355.4
XS Rating Curve= 0 ,0
Exp/Cntr=0.3,0.1

Type RM Length L Ch R = 1 ,9363    ,286,278.9,271
XS GIS Cut Line= 3
2484854.68475319666429.8289988852485310.97441628666452.097996776
2485559.91656775666400.494705499
#Sta/Elev= 30
       0 1908.44     4.9 1907.23    16.1 1906.17    28.1 1903.76    52.1 1895.75
    92.2 1883.58     150 1862.64   196.8 1842.82   228.3 1835.23   240.3 1830.64
   251.6 1830.54   264.4 1830.51   272.4 1829.78   280.4 1830.69   288.4 1830.17
   296.4 1831.43   302.1 1831.68   324.4 1830.91   340.5 1829.67   356.5  1831.5
   372.5 1835.01   384.5 1836.03   472.9 1839.04   532.3    1843   546.5 1842.87
   599.6 1847.95   652.7 1855.63   693.5 1864.27   705.8 1866.12   711.1 1867.75
#Mann= 3 ,-1 , 0
       0     .05       0   251.6    .045       0   280.4     .05       0
#XS Ineff= 2 , 0
                          302.43          1835.6
Permanent Ineff=
       F       F
Bank Sta=251.6,280.4
XS Rating Curve= 0 ,0
Exp/Cntr(USF)=0,0
Exp/Cntr=0.3,0.1

Type RM Length L Ch R = 1 ,9084    ,284.5,287.9,291.2
XS GIS Cut Line= 3
2484898.46208059666791.748507108     2485207.196      666692.916
2485545.78286255666583.768985784
#Sta/Elev= 30
       0 1889.67     4.5 1888.74    58.2 1882.54    75.9  1878.7    84.3 1876.08
    93.2 1875.09   101.1 1873.47   130.5 1865.02   180.9 1847.68   201.3 1841.91
   222.9 1837.14   249.1 1829.96   269.1 1822.22   281.7 1820.54   306.9 1821.11
   311.1 1820.55   315.3 1819.16   319.5 1817.93   323.7 1817.52   332.1 1817.88
   338.9  1819.3   357.3  1820.6   374.1 1824.56   408.1 1827.42   445.6 1832.21
     454 1833.87   466.6 1834.34   512.8 1844.56     538 1849.29   679.9 1868.21
#Mann= 3 ,-1 , 0
       0     .05       0   315.3    .045       0   338.9     .05       0
#XS Ineff= 2 , 0
          306.45 1824.14
Permanent Ineff=
       F       F
Bank Sta=315.3,338.9
XS Rating Curve= 0 ,0
Exp/Cntr=0.3,0.1

Type RM Length L Ch R = 1 ,8796    ,127.8,116.9,104.5
XS GIS Cut Line= 3
2484870.55308784667003.1042764862485340.07354385666960.800072517
2485575.11493686666864.978513758
#Sta/Elev= 30
       0 1884.05    20.3 1883.39    48.3 1880.36    72.5 1875.67   116.7 1869.31
   141.2 1864.19   156.8 1860.65   180.9 1854.03     189 1851.49     201  1846.2
   214.1 1843.67   237.1 1836.21   261.2 1830.81   317.5 1819.68   325.5 1817.52
   329.5 1815.44   333.5 1812.13   337.6 1810.44   349.6 1809.76   353.1 1809.07
   361.9 1807.62   373.7 1808.05   379.6 1809.24   393.8 1812.07   449.9  1813.6
   487.3 1816.94   500.2 1818.91   508.9 1819.37   649.8 1837.16   725.2 1847.58
#Mann= 3 ,-1 , 0
       0     .05       0   353.1    .045       0   379.6     .05       0
Bank Sta=353.1,379.6
XS Rating Curve= 0 ,0
Exp/Cntr=0.3,0.1

Type RM Length L Ch R = 1 ,8679    ,287.7,298.7,297.1
XS GIS Cut Line= 3
2485046.84887916667195.6070118132485380.05028438667005.843784341
2485581.60105212 666975.54611613
#Sta/Elev= 30
       0 1847.72    22.9 1843.49    41.9 1839.51      62 1834.69    78.1 1831.54
    85.5 1829.74    98.4  1828.5     115 1825.16   124.2 1824.12   132.4  1822.3
   147.2 1819.85     161 1816.27     184 1811.43   199.9 1806.47   205.8 1805.78
   216.2 1805.35     230  1806.2   243.9 1806.47   255.6 1808.36   262.3 1808.87
   276.1 1807.96   285.3 1809.15   292.4 1809.57   322.1 1809.41   331.3 1808.77
   335.9 1808.94   346.5 1810.78   388.4 1815.02   483.4 1825.72   587.3  1840.5
#Mann= 6 ,-1 , 0
       0     .05       0   199.9    .045       0   243.9     .05       0
  343.34      .1       0  445.19     .05       0  544.51      .1       0
#XS Ineff= 2 , 0
                          260.57          1810.8
Permanent Ineff=
       F       F
Bank Sta=199.9,243.9
XS Rating Curve= 0 ,0
Exp/Cntr=0.3,0.1

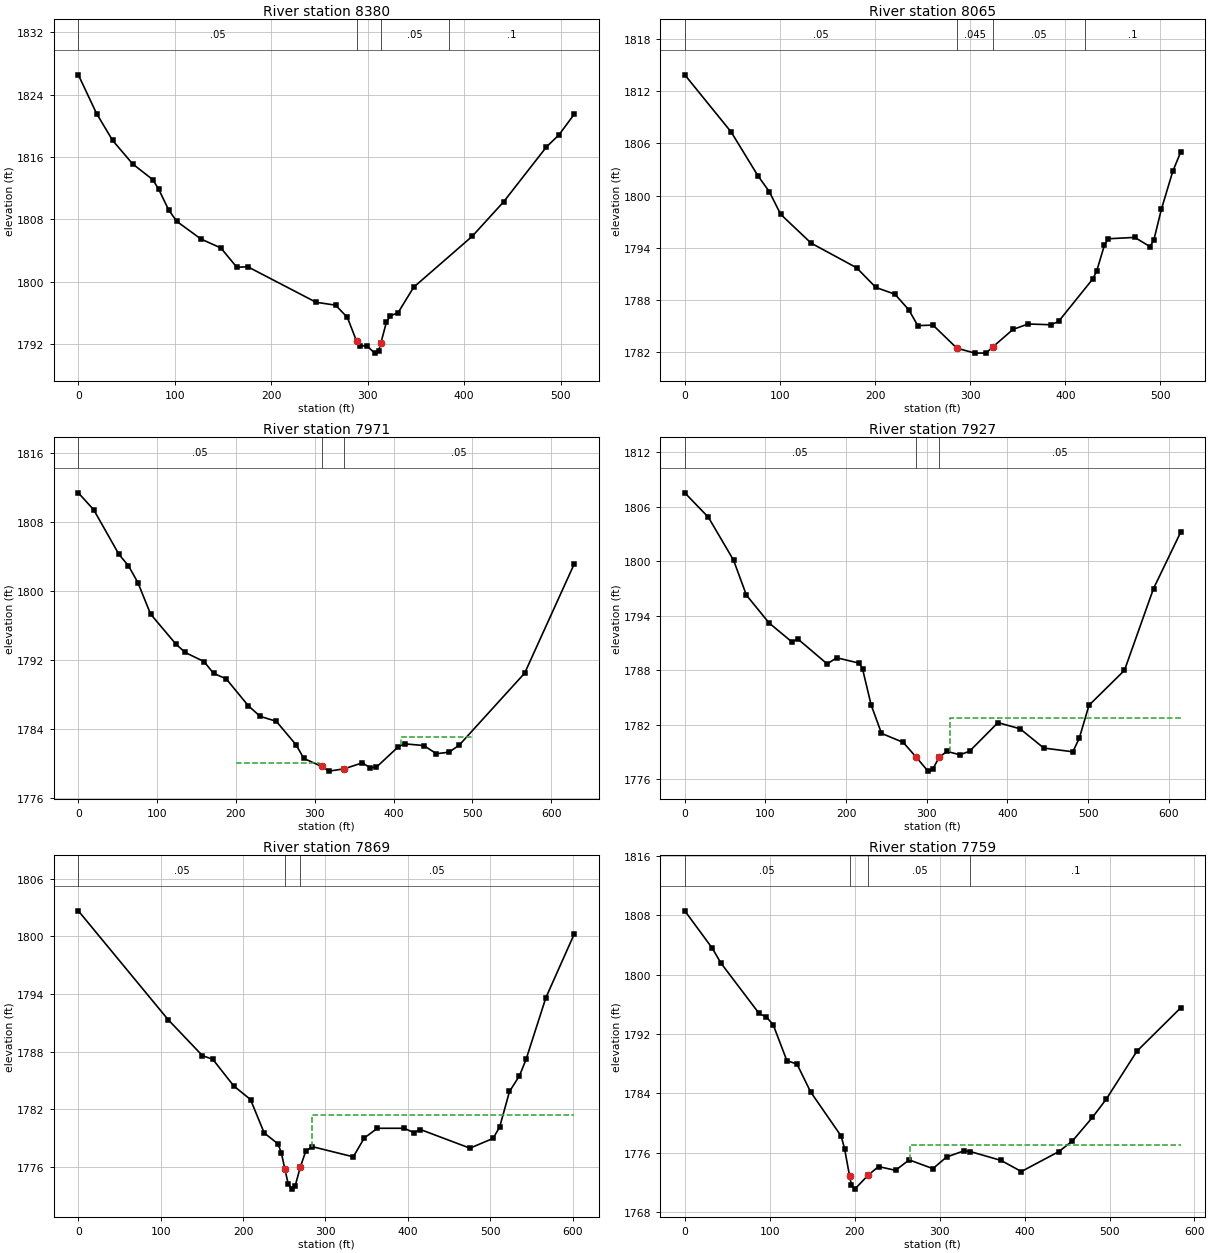
Type RM Length L Ch R = 1 ,8380    ,311.5,315.6,317.4
XS GIS Cut Line= 3
2485112.57728357  667365.65178562485309.72259982667309.604189581
2485615.08760332667261.184544492
#Sta/Elev= 30
       0 1826.54    18.9 1821.58    35.5 1818.14    56.3 1815.12    77.1 1813.11
    83.2  1811.9    93.7 1809.21   102.1 1807.75     127  1805.5   147.8 1804.34
   164.4 1801.86   175.6 1801.94   246.5 1797.38   266.7 1797.01   278.9 1795.45
   288.6 1792.37   292.1 1791.76   299.2 1791.81   307.2 1790.86   311.3 1791.12
   313.6 1792.11   319.4 1794.82   323.4 1795.63   331.5 1796.04   347.7 1799.31
   408.5 1805.85   440.9 1810.25   485.4  1817.3   498.4 1818.85   514.1 1821.48
#Mann= 4 ,-1 , 0
       0     .05       0   288.6    .045       0   313.6     .05       0
  384.73      .1       0
Bank Sta=288.6,313.6
XS Rating Curve= 0 ,0
Exp/Cntr(USF)=0,0
Exp/Cntr=0.3,0.1

Type RM Length L Ch R = 1 ,8065    ,80.2,93.6,116
XS GIS Cut Line= 2
2485117.98704503667612.593607455 2485638.9129016667596.965831758
#Sta/Elev= 30
       0 1813.89    48.8 1807.31    76.8  1802.3    88.8 1800.47   100.8 1797.86
   132.8 1794.55   180.6 1791.72   200.8 1789.46   220.9 1788.68   235.5 1786.88
   244.9 1785.07   260.9 1785.13     286 1782.48   304.9 1781.91   316.7 1781.92
   323.6  1782.6   344.9 1784.63   360.9 1785.26   384.9 1785.17   392.9 1785.55
     429 1790.45     433 1791.36     441 1794.28     445 1795.05     473 1795.21
     489 1794.15     493 1794.89     501 1798.45     513 1802.82   521.2 1804.99
#Mann= 4 ,-1 , 0
       0     .05       0     286    .045       0   323.6     .05       0
  421.11      .1       0
Bank Sta=286,323.6
XS Rating Curve= 0 ,0
Exp/Cntr(USF)=0,0
Exp/Cntr=0.5,0.3

Type RM Length L Ch R = 1 ,7971    ,44.7,44,43.3
XS GIS Cut Line= 4
2485123.17503608667645.2579050732485372.75163979667641.741418415
2485446.42543951 667736.847596232485705.56262347667743.966707041
#Sta/Elev= 30
       0 1811.41    19.6 1809.43    51.6 1804.25    63.6 1802.94    75.6 1800.98
    91.6 1797.34   123.6 1793.86   135.6 1792.87   159.5 1791.81   171.6 1790.44
   187.6 1789.81   215.6 1786.69   230.7 1785.45   251.1 1784.88   276.4 1782.13
   286.1 1780.56   308.9 1779.63   318.2 1779.09   337.4 1779.36   360.2 1780.05
   370.2  1779.5   378.2 1779.55   406.2 1781.94   414.2 1782.26   438.3 1782.06
   454.3 1781.11   470.3 1781.29   483.3 1782.11   566.3 1790.47   629.1 1803.13
#Mann= 3 ,-1 , 0
       0     .05       0   308.9    .045       0   337.4     .05       0
#XS Ineff= 3 ,-1
     200     305    1780     360     410    1780     410     500    1783
Permanent Ineff=
       F       F       F
Bank Sta=308.9,337.4
XS Rating Curve= 0 ,0
Exp/Cntr=0.5,0.3

Type RM Length L Ch R = 1 ,7927    ,65.9,57.7,43.9
XS GIS Cut Line= 4
2485134.31643344667679.2480800892485358.68664166667682.596889167
2485418.96520507667758.279974328 2485712.3208803667764.307830669
#Sta/Elev= 30
       0 1807.54    29.2 1804.85    60.4 1800.13    76.4 1796.27   104.4 1793.22
   132.4 1791.15   140.4 1791.43   176.4 1788.71   188.4 1789.38   216.5 1788.78
   220.5 1788.09   230.9 1784.21   243.8 1781.06   270.8 1780.06   286.1 1778.51
   301.5  1776.9   307.2 1777.08   315.21778.417   324.9 1779.07   341.1  1778.7
     353 1779.09   388.2 1782.24   415.6 1781.56     445 1779.44     481 1779.03
     489 1780.53     501 1784.15     545    1788     581    1797   614.6 1803.19
#Mann= 3 ,-1 , 0
       0     .05       0   286.1    .045       0   315.2     .05       0
#XS Ineff= 2 , 0
                          328.83         1782.77
Permanent Ineff=
       F       F
Bank Sta=286.1,315.2
XS Rating Curve= 0 ,0
Exp/Cntr(USF)=0,0
Exp/Cntr=0.5,0.3

Type RM Length L Ch R = 1 ,7869    ,114,110.7,104.2
XS GIS Cut Line= 3
2485129.89392175667718.2671383592485484.86768402667820.219770288
2485717.05178009667806.080354181
#Sta/Elev= 30
       0 1802.66   109.1 1791.33   150.7 1787.59   163.2 1787.22   188.7 1784.44
     209 1783.03   225.6 1779.56   242.3 1778.42   246.4  1777.5   250.6 1775.84
   254.7 1774.28   258.9 1773.71   263.1    1774   269.5 1776.01     276 1777.64
   283.9 1778.13   333.8 1777.07   347.1 1779.03     363 1780.04   395.5 1780.04
   407.3 1779.59   415.3 1779.91   475.4 1777.97   503.5 1778.99   511.5 1780.18
   523.4 1783.87   535.5  1785.5   543.5  1787.2   567.6 1793.63   601.9 1800.23
#Mann= 3 ,-1 , 0
       0     .05       0   250.6    .045       0   269.5     .05       0
#XS Ineff= 2 , 0
                          283.06          1781.4
Permanent Ineff=
       F       F
Bank Sta=250.6,269.5
XS Rating Curve= 0 ,0
Exp/Cntr(USF)=0,0
Exp/Cntr=0.3,0.1

Type RM Length L Ch R = 1 ,7759    ,327.8,324.8,316.4
XS GIS Cut Line= 3
 2485161.0826934667941.0198151492485242.89322557667898.520439333
2485734.19296539      667883.182
#Sta/Elev= 30
       0 1808.59    32.5 1803.53    42.4 1801.57    87.5 1794.76      96 1794.29
     104 1793.26   120.1 1788.42   132.1 1787.94   148.1  1784.2   184.1 1778.24
   188.1 1776.54   193.9 1772.92   196.1 1771.69   200.1  1771.1   216.1 1773.01
   228.1 1774.14   248.1 1773.63   264.1 1775.04   292.1 1773.86   308.1 1775.42
   328.2 1776.24   336.1 1776.16   372.2 1774.97   396.2 1773.47   440.2 1776.15
   456.2 1777.57   479.8 1780.75   496.2 1783.23   532.3 1789.69   583.7 1795.51
#Mann= 4 ,-1 , 0
       0     .05       0   193.9    .045       0   216.1     .05       0
   336.1      .1       0
#XS Ineff= 2 , 0
                          264.59         1777.04
Permanent Ineff=
       F       F
Bank Sta=193.9,216.1
XS Rating Curve= 0 ,0
Exp/Cntr=0.3,0.1

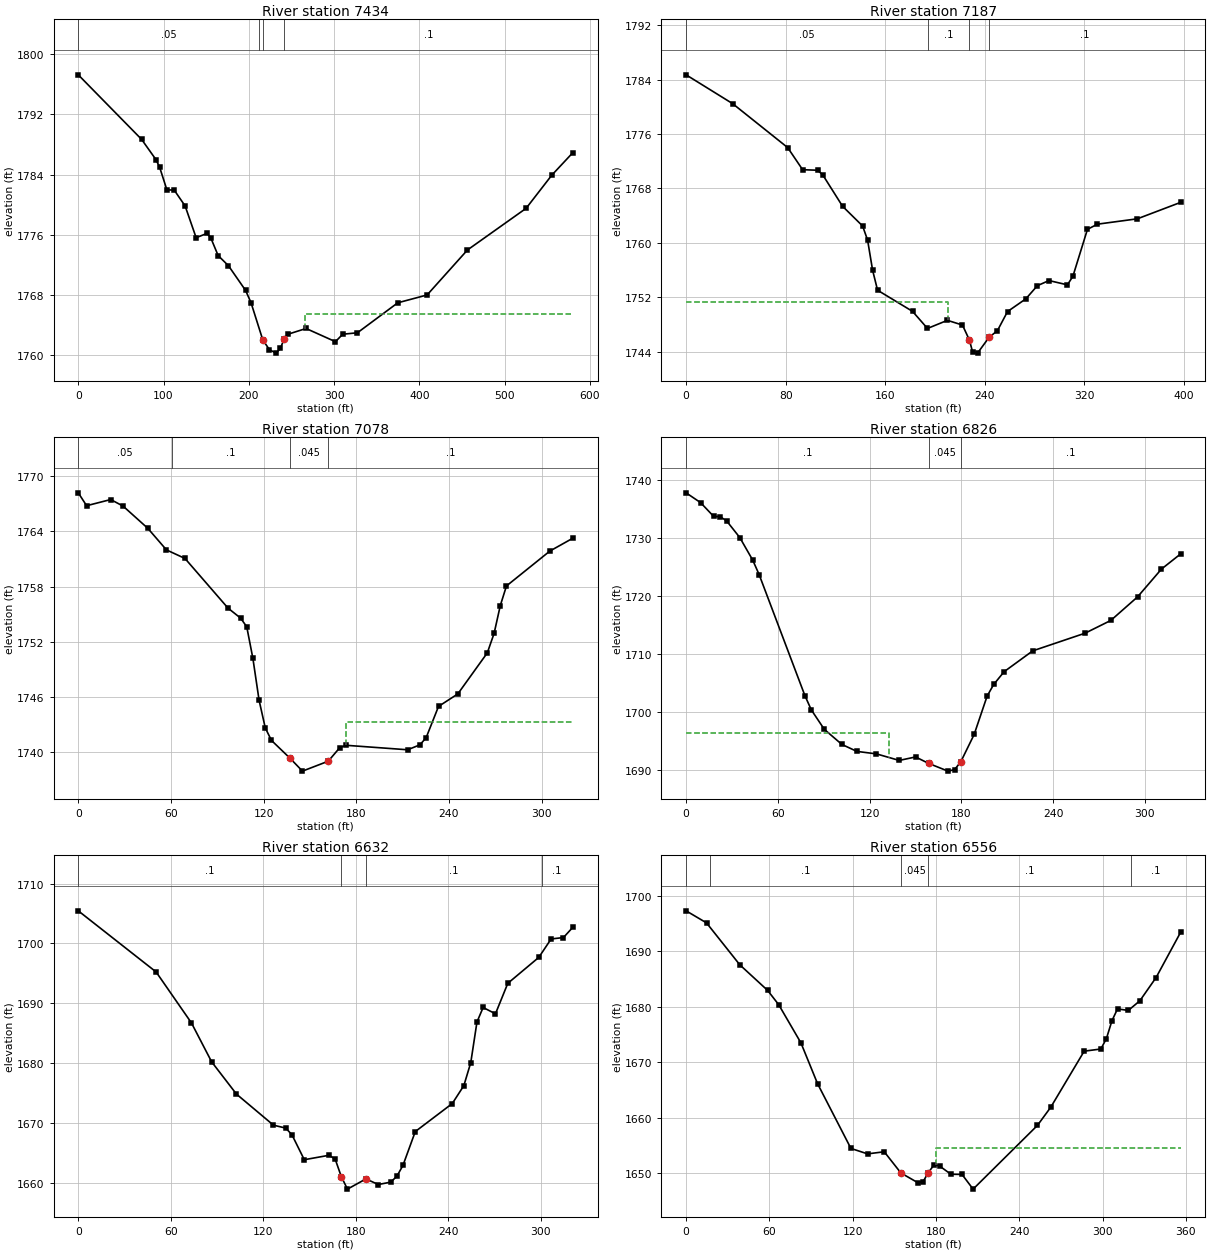
Type RM Length L Ch R = 1 ,7434    ,240.1,247.2,253
XS GIS Cut Line= 3
2485237.98213273668278.214202363      2485454.06      668193.897
2485777.70733245668066.048546213
#Sta/Elev= 30
       0 1797.24    74.2 1788.68      91    1786    95.3 1785.01   103.9 1781.97
   112.5 1781.94   125.3 1779.83   138.2 1775.62   151.1  1776.2   155.4 1775.59
     164 1773.25   176.1  1771.9   196.2 1768.62   202.6 1766.98   216.3 1762.07
   224.1 1760.76   231.9  1760.3     237 1760.92   241.3 1762.18   245.6  1762.8
   267.1 1763.57   301.5 1761.82   310.1 1762.81   327.3    1763   374.6 1766.98
     409 1768.02   456.3 1773.99   525.1 1779.52   555.2 1783.92   579.9 1786.91
#Mann= 4 ,-1 , 0
       0     .05       0  211.67      .1       0   216.3    .045       0
   241.3      .1       0
#XS Ineff= 2 , 0
                           266.4         1765.55
Permanent Ineff=
       F       F
Bank Sta=216.3,241.3
XS Rating Curve= 0 ,0
Exp/Cntr=0.3,0.1

Type RM Length L Ch R = 1 ,7187    ,110.9,109.2,107
XS GIS Cut Line= 2
2485277.46797544 668405.634005442485673.42928849668438.406890328
#Sta/Elev= 30
       0 1784.69    37.4 1780.45    81.6 1773.99    93.6 1770.74   105.6 1770.66
   109.7    1770   125.7 1765.36   141.8 1762.46   145.8 1760.38   149.8 1755.97
   153.8 1753.02   181.9 1749.91   193.9  1747.4   209.9 1748.59     222  1747.9
   227.6 1745.68   230.1 1743.97   234.1 1743.77   243.3 1746.07   250.1 1747.08
   258.2 1749.88   272.9 1751.75   282.2 1753.69   291.5 1754.44   306.3 1753.81
   310.7 1755.06   322.4 1761.97   330.4 1762.73   362.5 1763.52   397.3 1765.94
#Mann= 4 ,-1 , 0
       0     .05       0  194.09      .1       0   227.6    .045       0
   243.3      .1       0
#XS Ineff= 2 , 0
          210.28 1751.34
Permanent Ineff=
       F       F
Bank Sta=227.6,243.3
XS Rating Curve= 0 ,0
Exp/Cntr(USF)=0,0
Exp/Cntr=0.3,0.1

Type RM Length L Ch R = 1 ,7078    ,243.8,251.5,253.1
XS GIS Cut Line= 2
2485325.75472371668518.1722682462485645.68428305668534.111931338
#Sta/Elev= 30
       0 1768.19     5.4 1766.79      21 1767.46      29 1766.75      45 1764.34
    57.1 1761.99    69.1 1761.06      97 1755.66   105.1 1754.58   109.1 1753.64
   113.1 1750.19   117.1 1745.65   121.1 1742.65   125.1 1741.29   137.2 1739.34
   145.2 1737.95   161.9 1739.03   169.2 1740.47   173.2 1740.76   213.3 1740.27
   221.3 1740.81   225.3 1741.59   233.3 1744.98   245.8 1746.34   264.9  1750.8
   269.3 1752.92   273.3 1755.93   277.3 1758.07   305.4 1761.86   320.3 1763.26
#Mann= 4 ,-1 , 0
       0     .05       0   60.74      .1       0   137.2    .045       0
   161.9      .1       0
#XS Ineff= 2 , 0
                          173.24         1743.24
Permanent Ineff=
       F       F
Bank Sta=137.2,161.9
XS Rating Curve= 0 ,0
Exp/Cntr(USF)=0,0
Exp/Cntr=0.3,0.1

Type RM Length L Ch R = 1 ,6826    ,195.7,194.5,188.1
XS GIS Cut Line= 2
2485305.81040115668705.0752229582485609.66418774668816.122926408
#Sta/Elev= 30
       0 1737.84     9.5 1736.14      18 1733.77    22.3 1733.71    26.5 1732.99
    35.1 1730.12    43.6  1726.2    47.8 1723.69    77.7  1702.8    81.9 1700.33
    90.4 1696.97   101.9 1694.36   111.7 1693.16   124.5 1692.73   139.4  1691.6
   150.1  1692.2   158.6 1691.09   171.3 1689.75   175.6 1690.01   179.7 1691.38
   188.4 1696.08   196.9 1702.72   201.2 1704.73     208 1706.93   226.7 1710.53
     261 1713.59   277.8 1715.79   295.3 1719.86   310.9 1724.66   323.5 1727.29
#Mann= 3 ,-1 , 0
       0      .1       0   158.6    .045       0   179.7      .1       0
#XS Ineff= 2 , 0
          132.78 1696.35
Permanent Ineff=
       F       F
Bank Sta=158.6,179.7
XS Rating Curve= 0 ,0
Exp/Cntr(USF)=0,0
Exp/Cntr=0.3,0.1

Type RM Length L Ch R = 1 ,6632    ,71.1,75.1,71.1
XS GIS Cut Line= 2
2485248.24483822668910.3654970512485568.86681259668900.057853205
#Sta/Elev= 30
       0 1705.46    50.5 1695.23    73.4 1686.71    86.5  1680.2   102.6  1674.8
   126.6  1669.6   134.6 1669.11   138.6 1667.99   146.6 1663.82   162.6 1664.56
   166.6 1663.95   170.6    1661   174.6  1658.9   186.6 1660.61   194.6 1659.67
   202.6 1660.07   206.6 1661.03   210.6 1662.87   218.6 1668.53   242.6 1673.22
   250.1 1676.22   254.6 1680.08   258.6 1686.86   262.6 1689.29   270.6 1688.23
   278.6 1693.33   298.7 1697.67   306.7 1700.75   314.7 1700.99   320.8 1702.71
#Mann= 4 ,-1 , 0
       0      .1       0   170.6    .045       0   186.6      .1       0
  300.47      .1       0
Bank Sta=170.6,186.6
XS Rating Curve= 0 ,0
Exp/Cntr(USF)=0,0
Exp/Cntr=0.3,0.1

Type RM Length L Ch R = 1 ,6556    ,203.2,207.1,206.3
XS GIS Cut Line= 2
 2485240.0826206668967.106656389 2485596.1803356668975.560774941
#Sta/Elev= 30
       0 1697.25    14.7 1695.08    38.7 1687.52    58.7 1682.92    66.7 1680.34
    82.7 1673.46    94.7  1666.1   118.7 1654.45   130.7 1653.47   142.7 1653.85
   154.7 1650.03   166.9 1648.28   170.7 1648.48   174.4 1650.08   178.7 1651.54
   182.7 1651.26   190.7  1649.8   198.7 1649.77   206.7 1647.12     253 1658.59
   262.7  1661.9   286.7 1671.97   298.7 1672.36   302.7 1674.23   306.7 1677.46
   310.7 1679.58   318.5 1679.31   326.8 1681.05   338.5 1685.24   356.2 1693.41
#Mann= 5 ,-1 , 0
       0     .12       0   17.48      .1       0   154.7    .045       0
   174.4      .1       0  320.56      .1       0
#XS Ineff= 2 , 0
                          180.07         1654.56
Permanent Ineff=
       F       F
Bank Sta=154.7,174.4
XS Rating Curve= 0 ,0
Exp/Cntr(USF)=0,0
Exp/Cntr=0.3,0.1

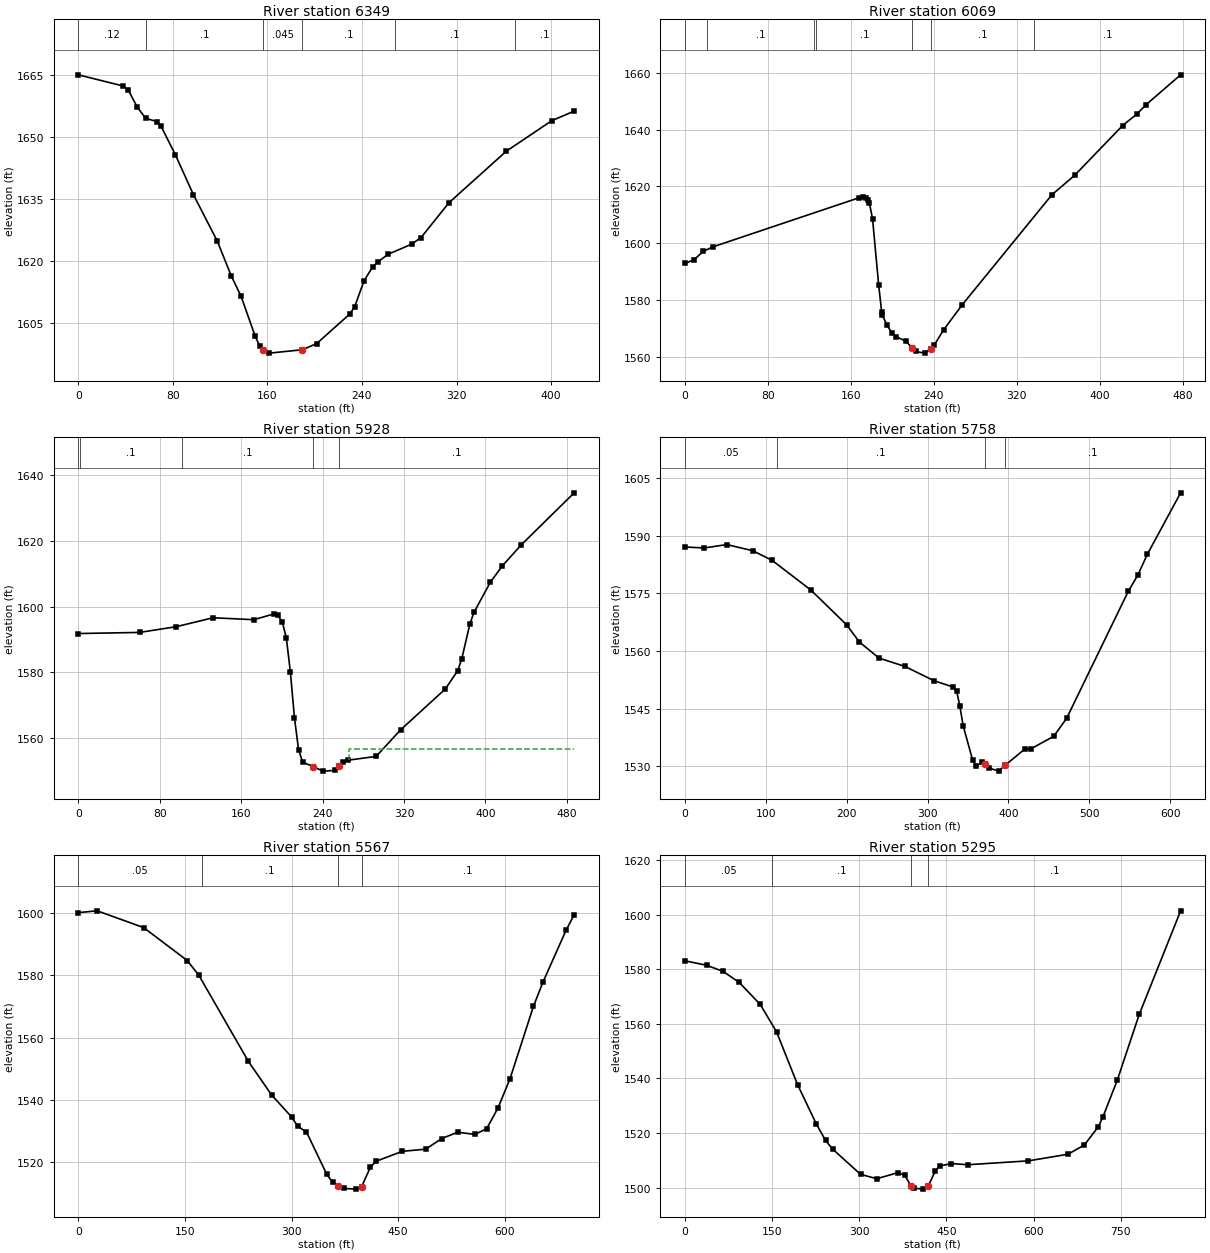
Type RM Length L Ch R = 1 ,6349    ,294.5,280.2,271.7
XS GIS Cut Line= 3
2485239.94707522669116.2416830872485307.53487041669163.013014768
2485644.04201604669185.711105146
#Sta/Elev= 30
       0 1665.05    37.5 1662.38    42.3 1661.34    49.9 1657.22    56.9 1654.55
    66.6 1653.74      70 1652.62    82.2 1645.67    97.4 1636.07   117.5 1624.91
   129.5 1616.38   137.7 1611.52   149.6 1601.89   153.6 1599.44   156.5 1598.65
   161.6 1597.79   189.6 1598.61   201.7 1600.11   229.7 1607.25   233.7 1608.95
   241.8 1615.31   249.1 1618.67   253.4 1619.84     262 1621.66   281.9 1624.12
   289.9 1625.71   313.6 1634.14     362 1646.57   400.6 1653.98   419.5 1656.27
#Mann= 6 ,-1 , 0
       0     .12       0   57.15      .1       0   156.5    .045       0
   189.6      .1       0  267.57      .1       0  369.53      .1       0
Bank Sta=156.5,189.6
XS Rating Curve= 0 ,0
Exp/Cntr(USF)=0,0
Exp/Cntr=0.3,0.1

Type RM Length L Ch R = 1 ,6069    ,136.3,141.2,151.3
XS GIS Cut Line= 2
2485323.10615958669500.3738072472485743.95251024669273.806575053
#Sta/Elev= 30
       0 1592.86     8.7 1594.08    17.8 1597.09    26.8 1598.65   167.7 1615.94
   172.1 1616.26   175.1 1615.88   176.8  1615.3     178    1614     181 1608.59
   186.9 1585.22   189.8 1575.78   190.4 1574.69   194.9 1571.13   199.5 1568.46
     204 1567.03   213.4 1565.38   219.4 1563.04   222.5 1561.85   231.2 1561.26
   237.1 1562.84   240.4 1564.03   249.4 1569.42   267.6 1578.35   353.9 1617.02
   375.9  1623.9   422.1 1641.42   435.7 1645.42   444.8 1648.78     478 1659.27
#Mann= 7 ,-1 , 0
       0     .05       0   21.76      .1       0  124.12      .1       0
  126.86      .1       0   219.4    .045       0   237.1      .1       0
  337.04      .1       0
Bank Sta=219.4,237.1
XS Rating Curve= 0 ,0
Exp/Cntr=0.3,0.1

Type RM Length L Ch R = 1 ,5928    ,168.7,169.9,169.3
XS GIS Cut Line= 2
2485346.62684875669528.9861330292485833.09345405669502.520333258
#Sta/Elev= 30
       0 1591.78    60.2 1592.12    96.3 1593.87   132.3 1596.58   172.4 1595.99
   192.1 1597.73   195.9 1597.35   200.4 1595.34   204.4 1590.43   208.4 1579.97
   212.4 1566.05   216.4 1556.47   220.4  1552.7   230.9 1551.27   240.5 1549.94
   252.5 1550.16   256.5 1551.52   260.4 1552.86   264.5 1553.25   292.6 1554.41
   316.6 1562.47   360.7 1574.95   372.7 1580.45   376.7    1584   384.7 1594.65
   388.7 1598.18   404.8 1607.36   416.7 1612.38   435.2 1618.74   487.2 1634.57
#Mann= 5 ,-1 , 0
       0     .05       0    1.94      .1       0  101.82      .1       0
   230.9    .045       0   256.5      .1       0
#XS Ineff= 2 , 0
                          265.84          1556.6
Permanent Ineff=
       F       F
Bank Sta=230.9,256.5
XS Rating Curve= 0 ,0
Exp/Cntr(USF)=0,0
Exp/Cntr=0.3,0.1

Type RM Length L Ch R = 1 ,5758    ,187.9,190.9,194.4
XS GIS Cut Line= 2
2485258.89049993669675.2351182652485871.71213003669675.030712254
#Sta/Elev= 30
       0 1587.11    23.9 1586.85    51.9 1587.73    83.9 1586.14   107.9 1583.63
   155.9 1575.88   199.9 1566.86   215.9 1562.34   240.1 1558.17   271.9 1556.02
   307.9 1552.29   331.9 1550.63   335.9 1549.64   339.9 1545.72   344.1 1540.49
   355.6 1531.73   359.9  1530.1   367.9 1531.03   371.6 1530.69   375.9 1529.57
   387.9 1528.74   395.9 1530.26   419.9 1534.43   427.9 1534.57   455.9  1537.8
   471.9 1542.48     548 1575.52   559.9 1579.79   571.7 1585.21   612.8 1601.21
#Mann= 4 ,-1 , 0
       0     .05       0  113.39      .1       0   371.6    .045       0
   395.9      .1       0
Bank Sta=371.6,395.9
XS Rating Curve= 0 ,0
Exp/Cntr(USF)=0,0
Exp/Cntr=0.3,0.1

Type RM Length L Ch R = 1 ,5567    ,277.2,272.2,267.4
XS GIS Cut Line= 3
2485224.78333167669778.7197081622485774.31922884669894.852759915
2485905.70392372669860.377365073
#Sta/Elev= 30
       0  1600.2    26.5 1600.78    91.9 1595.39   153.3 1584.78   169.6 1580.03
   239.1 1552.41   271.8  1541.6   300.5 1534.38   308.6  1531.5   320.9 1529.69
   349.6 1516.01   357.7 1513.48   365.2 1512.44     374 1511.52   390.4  1511.3
   398.6 1512.09   410.8 1518.33     419 1520.27   455.8 1523.46   488.5 1524.14
   511.4 1527.57   533.5  1529.6     558 1528.89   574.5 1530.75   590.4 1537.42
   607.2 1546.75   640.3 1570.12   653.7 1577.91   686.2 1594.58   697.5 1599.49
#Mann= 4 ,-1 , 0
       0     .05       0  173.87      .1       0   365.2    .045       0
   398.6      .1       0
Bank Sta=365.2,398.6
XS Rating Curve= 0 ,0
Exp/Cntr(USF)=0,0
Exp/Cntr=0.3,0.1

Type RM Length L Ch R = 1 ,5295    ,146.9,149.6,146.9
XS GIS Cut Line= 3
2485197.30431086670150.0468764052485937.44821346670095.645003748
2486042.22899625670059.623719101
#Sta/Elev= 30
       0 1583.09    37.5 1581.45    65.6 1579.23    93.7 1575.15   129.8 1567.09
   157.9 1557.04     194 1537.73     226 1523.46   242.1  1517.3   254.1 1514.17
   302.3  1504.9   330.3 1503.28   366.7 1505.53   378.5 1504.49   389.1 1500.67
   394.5 1499.82   410.5 1499.48     419 1500.64     431 1506.21   438.6 1507.95
   458.7 1508.84   486.8 1508.42     591 1509.83   659.2 1512.26   687.3 1515.64
   711.4 1522.33   719.4    1526   743.8  1539.3   781.7 1563.45   852.9 1601.38
#Mann= 4 ,-1 , 0
       0     .05       0  149.97      .1       0   389.1    .045       0
     419      .1       0
Bank Sta=389.1,419
XS Rating Curve= 0 ,0
Exp/Cntr=0.3,0.1

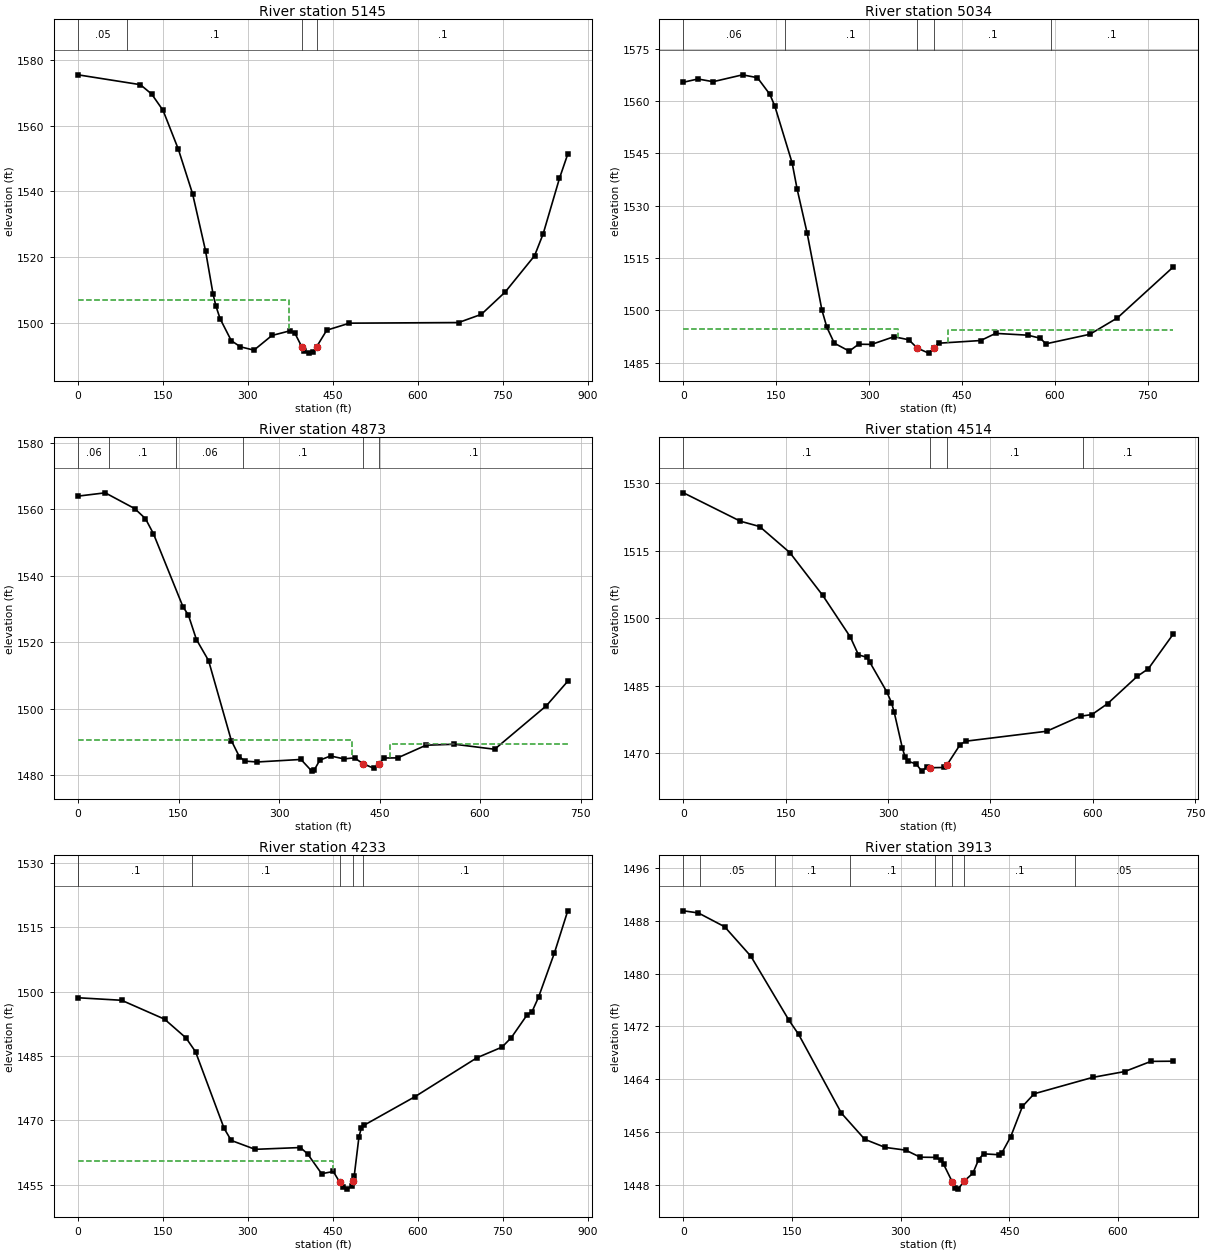
Type RM Length L Ch R = 1 ,5145    ,108.7,111.2,110.9
XS GIS Cut Line= 3
2485185.09118727670301.1405917592485907.94627713670238.014629217
2486036.19296629670183.421659178
#Sta/Elev= 30
       0 1575.54   110.1 1572.54   130.1 1569.67   150.2  1564.7   177.2 1552.86
   202.4 1539.25   225.2 1521.94   238.6 1508.63   243.6 1505.05     251 1501.19
   270.7 1494.53   286.7 1492.66   310.8 1491.64   342.5 1496.11   375.1 1497.56
   383.1 1496.78   395.3 1492.62   399.2 1491.35   407.2 1490.73   415.2 1491.12
   421.7 1492.74   439.3 1497.72   479.5 1499.86   672.2 1500.05   712.4 1502.55
   754.5 1509.35   806.4 1520.41   821.6  1527.1   850.4 1544.01     865 1551.38
#Mann= 4 ,-1 , 0
       0     .05       0   86.55      .1       0   395.3    .045       0
   421.7      .1       0
#XS Ineff= 2 , 0
          371.97    1507
Permanent Ineff=
       F       F
Bank Sta=395.3,421.7
XS Rating Curve= 0 ,0
Exp/Cntr=0.3,0.1

Type RM Length L Ch R = 1 ,5034    ,161.2,160.9,160.5
XS GIS Cut Line= 3
2485223.49027656670394.0526610962485797.82738627670361.398042818
2485991.83423604670455.520177854
#Sta/Elev= 30
       0 1565.41    23.3 1566.34    47.8 1565.56    95.4 1567.53   119.4 1566.71
   139.5 1561.94   147.5 1558.58   175.5 1542.26   183.6 1534.73   199.6 1522.27
   223.6 1500.09   231.6 1495.17   243.6 1490.62   267.7 1488.34   282.8 1490.32
   303.7 1490.27   339.9 1492.47   363.8  1491.6   377.6 1489.21   395.9 1487.77
   404.41489.167   411.9 1490.61     480 1491.38   504.1 1493.43   556.2 1492.91
   576.3 1492.04   585.2 1490.43   656.3 1493.17   700.8 1497.87   790.9 1512.45
#Mann= 5 ,-1 , 0
       0     .06       0  163.48      .1       0   377.6    .045       0
   404.4      .1       0  593.44      .1       0
#XS Ineff= 2 , 0
          346.73 1494.64  427.54         1494.48
Permanent Ineff=
       F       F
Bank Sta=377.6,404.4
XS Rating Curve= 0 ,0
Exp/Cntr(USF)=0,0
Exp/Cntr=0.3,0.1

Type RM Length L Ch R = 1 ,4873    ,358.5,359.2,357.5
XS GIS Cut Line= 3
2485262.21228951670525.6445544452485742.97857647670504.089696651
2485982.38404175670574.751422597
#Sta/Elev= 30
       0 1563.89    40.6 1564.88    84.6 1560.14   100.6 1557.13   112.6 1552.57
   156.7 1530.61   164.7 1528.15   176.7 1520.79   194.8 1514.48   228.8 1490.44
   240.7 1485.63   248.8 1484.26   267.6    1484   332.7 1484.76   348.9 1481.25
   352.9 1481.72   360.9 1484.55   376.9 1485.81   396.9 1484.92   412.7 1485.25
     425 1483.51     441 1482.15     449 1483.38     457 1485.19     477 1485.23
   519.4 1489.04   561.8 1489.33   621.8 1487.82   699.1 1500.92   730.9 1508.26
#Mann= 6 ,-1 , 0
       0     .06       0   46.43      .1       0  146.41     .06       0
   246.4      .1       0     425    .045       0     449      .1       0
#XS Ineff= 2 , 0
          408.28 1490.66  466.35         1489.55
Permanent Ineff=
       F       F
Bank Sta=425,449
XS Rating Curve= 0 ,0
Exp/Cntr(USF)=0,0
Exp/Cntr=0.3,0.1

Type RM Length L Ch R = 1 ,4514    ,281.5,281.6,280
XS GIS Cut Line= 3
2485271.93114981670844.3581235942485730.95623969670790.738749063
2485977.79519851670723.967404493
#Sta/Elev= 30
       0  1527.9    83.4 1521.58   111.6  1520.4   155.9 1514.59   204.2 1505.05
   244.5 1495.82   256.5 1491.83   268.6 1491.29   272.7 1490.31   297.9 1483.63
   304.9  1481.2   308.9 1479.06     321 1470.99     325 1469.04     329 1468.13
   341.1 1467.55   349.2 1465.94   357.2 1466.91   361.8  1466.7   381.4 1466.75
   386.1 1467.29   405.6 1471.85   413.6  1472.6   532.4 1474.82   582.1 1478.17
   598.7 1478.53   621.7 1480.96     665 1487.02   681.5 1488.74   717.9 1496.44
#Mann= 4 ,-1 , 0
       0      .1       0   361.8    .045       0   386.1      .1       0
  585.21      .1       0
Bank Sta=361.8,386.1
XS Rating Curve= 0 ,0
Exp/Cntr=0.3,0.1

Type RM Length L Ch R = 1 ,4233    ,313.1,320,325.5
XS GIS Cut Line= 4
2485305.58559176 671130.563310862485699.84905352671001.336689238
2485912.72676403670949.8409101152486142.07406367670922.943599255
#Sta/Elev= 30
       0 1498.58      77 1497.99   152.8 1493.59   190.6 1489.23   207.5 1486.01
     258 1468.14   270.6 1465.34   312.7 1463.27   392.7 1463.69   405.3 1462.22
   430.2 1457.59   450.8 1458.11   462.4 1455.55   467.3 1454.46   475.2    1454
   483.7 1454.75   485.6 1455.92   487.8 1457.16   496.1 1466.17   500.2 1468.21
   504.3 1468.83   594.7 1475.51   704.4  1484.6   748.7 1487.08   765.2  1489.3
     793 1494.59   801.7 1495.33   813.2 1498.71   841.3 1509.04   864.8 1518.83
#Mann= 6 ,-1 , 0
       0      .1       0      .8      .1       0  201.87      .1       0
   462.4    .045       0   485.6      .1       0  502.66      .1       0
#XS Ineff= 2 , 0
          450.19 1460.49
Permanent Ineff=
       F       F
Bank Sta=462.4,485.6
XS Rating Curve= 0 ,0
Exp/Cntr=0.3,0.1

Type RM Length L Ch R = 1 ,3913    ,78.7,66.9,55.9
XS GIS Cut Line= 2
2485302.37618292671240.3806788462485973.22087673671324.944712745
#Sta/Elev= 30
       0 1489.53    20.5 1489.21    56.8 1487.12    93.1 1482.64   145.5 1472.97
     159  1470.8   218.1 1458.86   250.3  1454.9   278.6 1453.67   306.8 1453.26
   326.9 1452.19   348.1 1452.16   355.2 1451.76   359.2 1451.12   371.2 1448.43
   375.3 1447.55   379.3 1447.35   387.4 1448.56   399.5 1449.74   407.6 1451.84
   414.3  1452.7   435.8 1452.56   439.8 1452.88   451.9 1455.31     468 1459.88
   484.2  1461.8   564.8 1464.28   609.2 1465.17   645.4 1466.71   676.2 1466.74
#Mann= 8 ,-1 , 0
       0      .1       0   22.45     .05       0  125.97      .1       0
  229.49      .1       0  346.78      .1       0   371.2    .045       0
   387.4      .1       0  540.06     .05       0
Bank Sta=371.2,387.4
XS Rating Curve= 0 ,0
Exp/Cntr=0.5,0.3