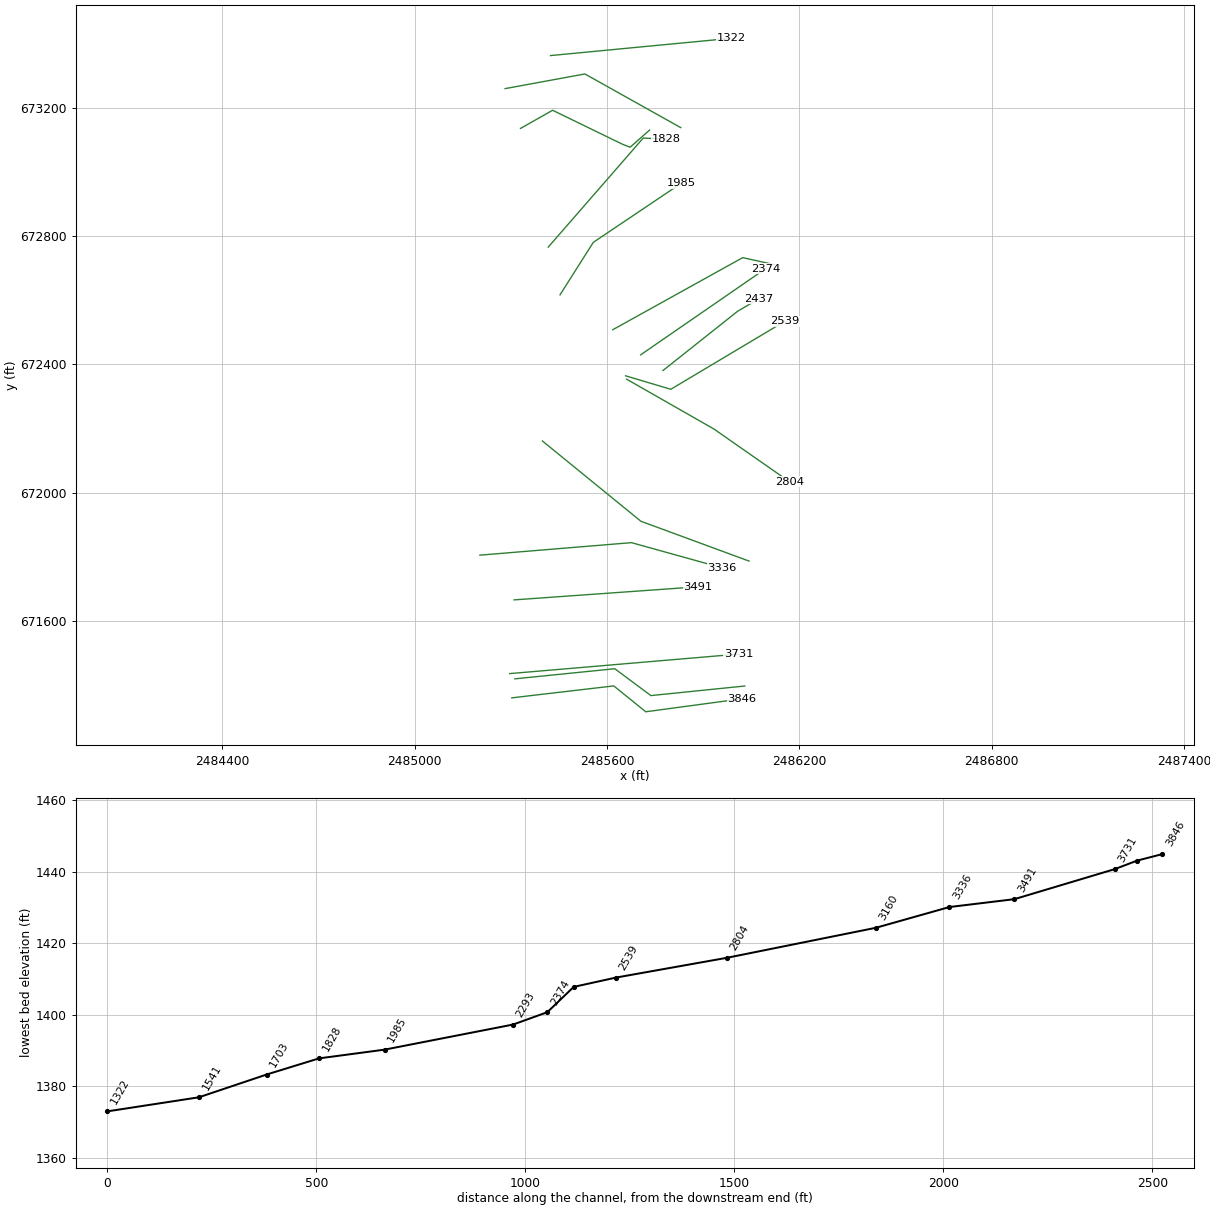
HEC-RAS study KESSNERRN.prj: KESSNERRN

--- KESSNERRN.g01 (geometry) --- (continued)

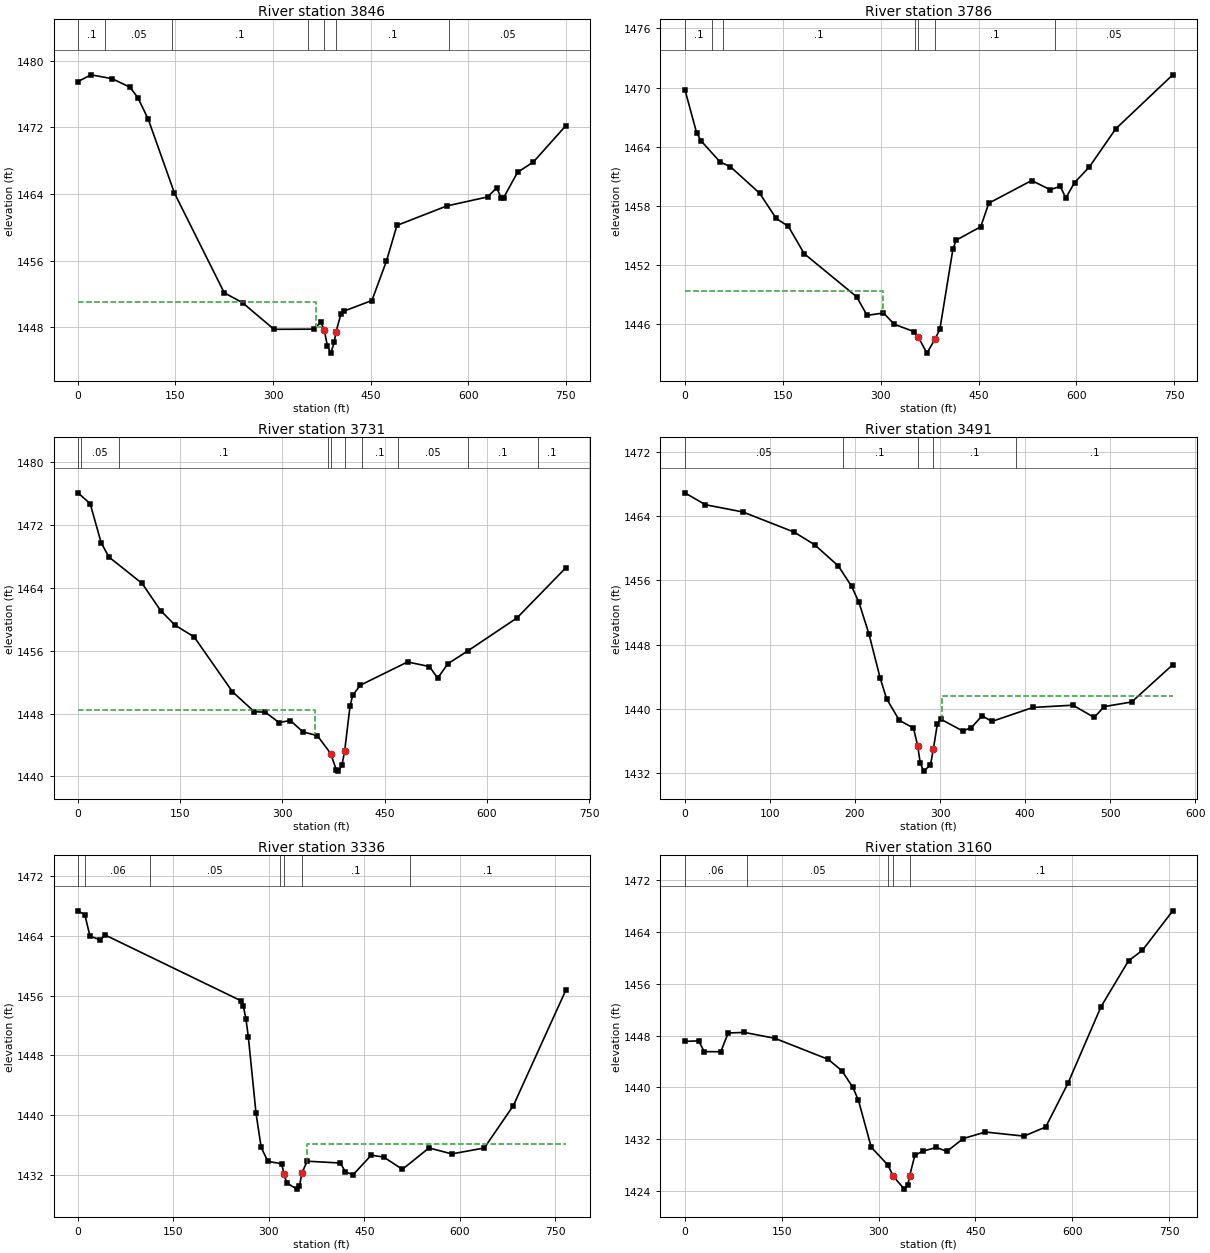
Type RM Length L Ch R = 1 ,3846    ,63.3,60.1,60.1
XS GIS Cut Line= 4
2485303.24635521671360.0510735142485621.28150466671397.297200752
2485721.04015618671316.604743094 2486020.1206445671357.007755603
#Sta/Elev= 30
       0  1477.5    20.1 1478.31    52.6 1477.85      80 1476.82    92.1 1475.58
   108.2 1472.96   148.5 1464.09     225 1452.13   253.2 1450.93   301.5 1447.74
   362.8 1447.76   373.5 1448.59   378.7 1447.71   383.8 1445.69     389 1444.88
   394.1 1446.18   396.9 1447.44   404.4 1449.56   409.6 1449.94   452.1  1451.2
   474.5 1455.94   490.6 1460.22   567.3 1462.56   629.9 1463.64     644 1464.73
   651.2  1463.5   654.8 1463.57   676.1  1466.6   700.5 1467.84   750.3  1472.2
#Mann= 7 ,-1 , 0
       0      .1       0   41.41     .05       0  144.67      .1       0
  354.53      .1       0   378.7    .045       0   396.9      .1       0
  570.84     .05       0
#XS Ineff= 3 ,-1
       0  365.41    1451  365.41     378    1448   411.2   746.7    1449
Permanent Ineff=
       F       F       F
Bank Sta=378.7,396.9
XS Rating Curve= 0 ,0
Exp/Cntr(USF)=0,0
Exp/Cntr=0.5,0.3

Type RM Length L Ch R = 1 ,3786    ,39.9,54.1,64.9
XS GIS Cut Line= 4
2485312.92405283671419.3081747742485624.39294717671450.851617874
2485737.00938401671367.1359639122486029.68057319671396.959626018
#Sta/Elev= 30
       0 1469.81    17.9 1465.44    24.9  1464.6    54.1 1462.45    69.6 1461.99
   114.4  1459.3     140 1456.73   158.6 1455.93   182.8 1453.16   263.2 1448.79
   279.2  1446.9   304.3 1447.14     321 1445.99   350.9 1445.26   357.9 1444.68
   370.8 1443.07   383.3 1444.48   390.8 1445.51   410.7 1453.59   415.7 1454.53
   453.4 1455.89   465.7 1458.28   531.4 1460.58   559.7 1459.65   575.2 1459.98
   583.8 1458.82   597.1 1460.36     620 1461.97   660.2 1465.82   747.6  1471.3
#Mann= 7 ,-1 , 0
       0      .1       0   41.16     .05       0   58.53      .1       0
  352.82      .1       0   357.9    .045       0   383.3      .1       0
  566.62     .05       0
#XS Ineff= 2 , 0
          303.45 1449.35
Permanent Ineff=
       F       F
Bank Sta=357.9,383.3
XS Rating Curve= 0 ,0
Exp/Cntr=0.5,0.3

Type RM Length L Ch R = 1 ,3731    ,239,240,239.3
XS GIS Cut Line= 2
2485296.85488752671435.6833048652486010.09386045671496.490388951
#Sta/Elev= 30
       0 1476.11      18 1474.72      34 1469.77    45.4 1467.94    94.2 1464.57
   121.4 1461.11   142.4 1459.26   170.5 1457.76   226.7 1450.78   258.8 1448.23
   274.8 1448.18     295 1446.86   311.7 1447.11   330.2 1445.66   351.2  1445.2
   370.9  1442.9   379.3 1440.77     382 1440.67   387.3 1441.42   391.3 1443.21
   399.3    1449   403.3 1450.36   414.5 1451.62   483.6 1454.57   515.8 1453.99
   527.8 1452.51   542.7 1454.34     572 1455.98   644.2 1460.18   715.8 1466.56
#Mann= 10 ,-1 , 0
       0      .1       0    4.42     .05       0   60.04      .1       0
  367.22      .1       0   370.9    .045       0   391.3      .1       0
  416.27      .1       0  469.61     .05       0     572      .1       0
  674.39      .1       0
#XS Ineff= 2 , 0
          347.97  1448.4
Permanent Ineff=
       F       F
Bank Sta=370.9,391.3
XS Rating Curve= 0 ,0
Exp/Cntr=0.3,0.1

Type RM Length L Ch R = 1 ,3491    ,157.8,155.1,155.4
XS GIS Cut Line= 2
2485310.67376684671665.5187415232485882.88291036671706.286802369
#Sta/Elev= 30
       0 1466.89    24.1 1465.41    68.2 1464.51   128.4 1462.01   152.5 1460.44
   180.5 1457.79     196 1455.27   204.6  1453.3   216.6 1449.29   229.7 1443.83
   237.2 1441.29   252.2 1438.59   268.8 1437.64   273.8 1435.41   276.8 1433.28
   280.8 1432.28   288.8 1433.04   292.2 1435.03   296.8 1438.08   300.8 1438.75
   326.7 1437.27   336.9 1437.69   349.5 1439.16     361 1438.46   409.4  1440.2
   456.3 1440.48   481.3 1438.96   493.3 1440.31   525.4 1440.88   573.7 1445.51
#Mann= 5 ,-1 , 0
       0     .05       0  185.66      .1       0   273.8    .045       0
   292.2      .1       0  389.75      .1       0
#XS Ineff= 2 , 0
                          302.37         1441.66
Permanent Ineff=
       F       F
Bank Sta=273.8,292.2
XS Rating Curve= 0 ,0
Exp/Cntr=0.3,0.1

Type RM Length L Ch R = 1 ,3336    ,194,176.2,165.2
XS GIS Cut Line= 3
2485203.86074343671804.9989729932485676.28135858671843.966952737
2485958.21833759671765.660945985
#Sta/Elev= 30
       0 1467.38    10.9 1466.84    18.9 1463.99      35  1463.5      43 1464.13
   255.7 1455.35   259.8 1454.64     264 1452.89   267.7 1450.53   279.8 1440.28
   287.9 1435.68   298.5 1433.81     320 1433.49     324 1432.09     328 1430.93
     344 1430.09   348.1 1430.56   352.1 1432.27   360.1 1433.83   412.3 1433.59
   420.3 1432.42   432.3 1432.01   460.9 1434.64   480.7 1434.38   509.8 1432.74
   551.6 1435.61   587.4 1434.81   638.5  1435.6   684.2 1441.28   766.6 1456.74
#Mann= 7 ,-1 , 0
       0      .1       0   10.82     .06       0  113.14     .05       0
  317.79      .1       0     324    .045       0   352.1      .1       0
  521.29      .1       0
#XS Ineff= 2 , 0
                          359.18          1436.2
Permanent Ineff=
       F       F
Bank Sta=324,352.1
XS Rating Curve= 0 ,0
Exp/Cntr=0.3,0.1

Type RM Length L Ch R = 1 ,3160    ,353.1,356,358.1
XS GIS Cut Line= 3
2485398.75052438672160.9921607062485705.77084719671910.738407106
     2486042.904      671786.565
#Sta/Elev= 30
       0  1447.1    21.4 1447.18    29.9 1445.52    55.5  1445.5    67.1  1448.4
      92 1448.49   139.3 1447.58   221.9 1444.33   243.2 1442.56   260.2 1439.98
   268.7 1438.01   288.6 1430.75   314.2 1428.02   322.8 1426.25   339.8 1424.28
   345.2  1424.9   348.1 1426.35   356.1 1429.51   368.2 1430.13   389.5 1430.72
   405.7 1430.11   431.2  1432.1   465.3  1433.1     525 1432.47   558.7 1433.87
     593  1440.6   644.4 1452.47     687 1459.56   708.3 1461.15   755.4 1467.27
#Mann= 5 ,-1 , 0
       0     .06       0   96.03     .05       0  314.41      .1       0
   322.8    .045       0   348.1      .1       0
Bank Sta=322.8,348.1
XS Rating Curve= 0 ,0
Exp/Cntr=0.3,0.1

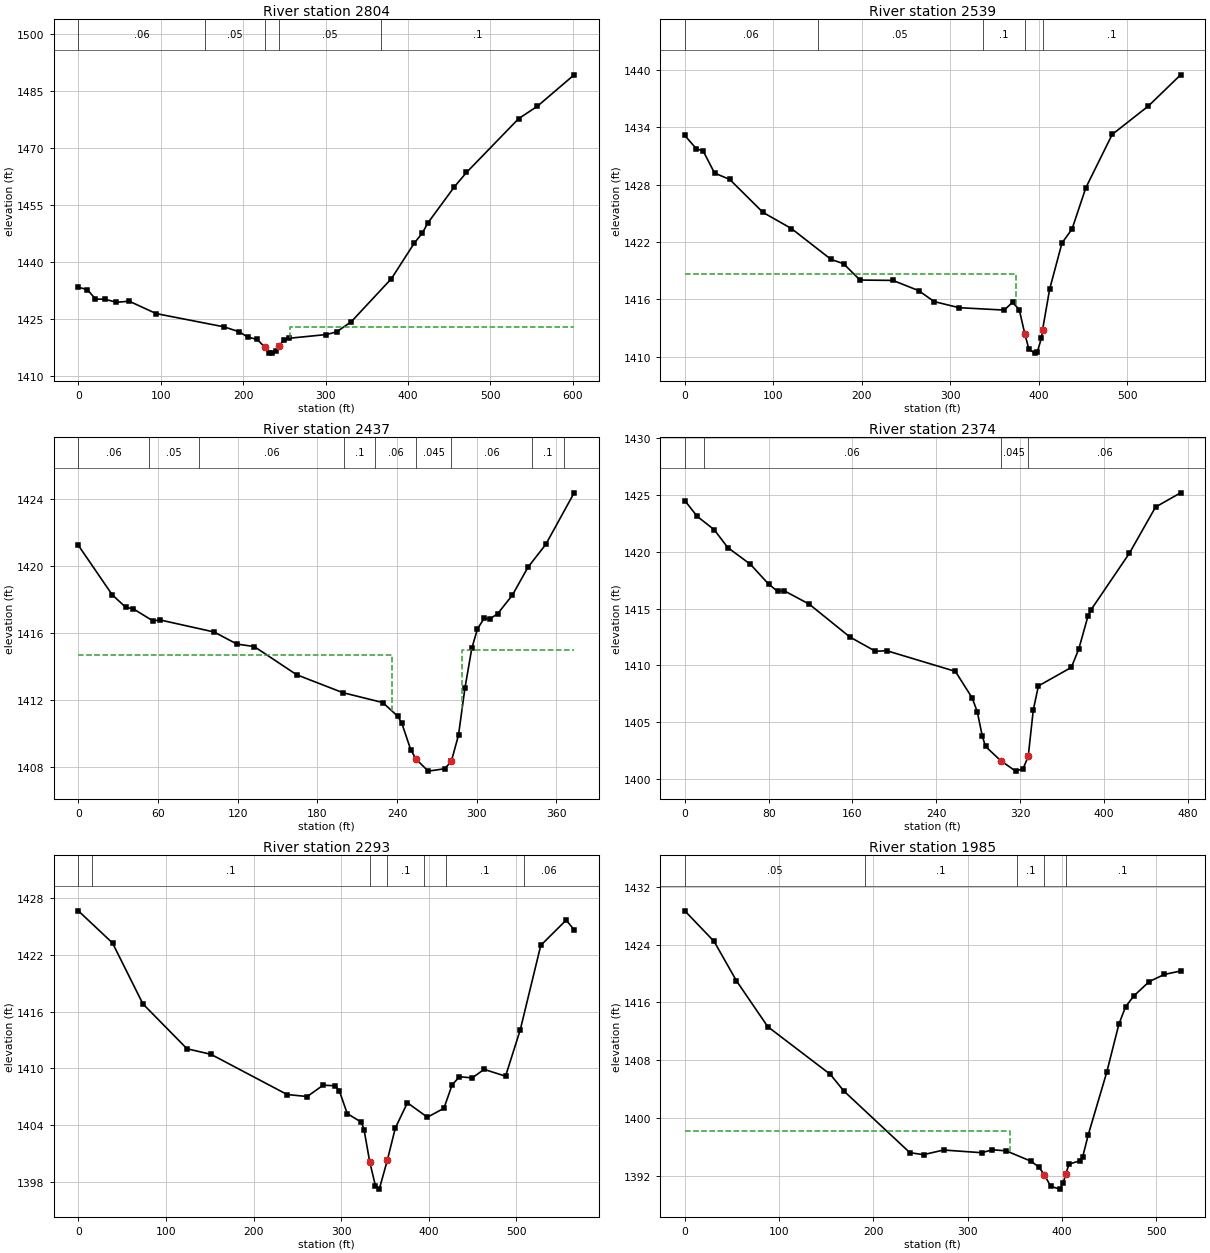
Type RM Length L Ch R = 1 ,2804    ,250.5,265.1,282.2
XS GIS Cut Line= 3
2485661.18840936672353.754290283 2485933.4370725672198.380053238
2486169.93591119672033.380863456
#Sta/Elev= 30
       0 1433.28      11 1432.63    20.8 1430.16    32.6  1430.1    46.1  1429.3
    61.7 1429.59    94.5 1426.32   176.8 1422.83   195.2 1421.53   205.6 1420.13
   217.3  1419.5   226.1 1417.48   231.9 1415.98   234.9  1415.9   239.8 1416.52
   243.2 1417.67   249.5 1419.37   255.4 1419.81   301.2  1420.8   313.5  1421.5
   331.3 1424.18   380.1 1435.56   407.7 1444.88   417.5 1447.55   424.4 1450.27
   456.5 1459.77   471.1 1463.52   534.5 1477.73   557.3 1481.01   601.8 1489.27
#Mann= 5 ,-1 , 0
       0     .06       0  153.16     .05       0   226.1    .045       0
   243.2     .05       0  367.27      .1       0
#XS Ineff= 2 , 0
                          256.96         1422.73
Permanent Ineff=
       F       F
Bank Sta=226.1,243.2
XS Rating Curve= 0 ,0
Exp/Cntr(USF)=0,0
Exp/Cntr=0.3,0.1

Type RM Length L Ch R = 1 ,2539    ,98.9,101.7,105.5
XS GIS Cut Line= 3
2485658.16143229672364.163936741 2485799.0784682672322.163333971
2486153.80998309672533.722230913
#Sta/Elev= 30
       0 1433.13    13.1 1431.74    20.8  1431.5    33.6  1429.2    50.7 1428.54
    88.3 1425.09   120.5  1423.4   165.3 1420.17   179.3 1419.73   197.9 1418.02
   235.1 1417.98     264 1416.92   281.7 1415.77   309.7 1415.13   360.9 1414.88
   370.2 1415.69   377.8 1414.93   384.2 1412.34   388.8 1410.77   395.3 1410.38
   398.2  1410.5   402.8 1411.94   404.1 1412.78   412.1 1417.05   426.1  1421.9
   437.4 1423.34     453 1427.66   482.8 1433.24   523.7 1436.21   560.1 1439.47
#Mann= 5 ,-1 , 0
       0     .06       0  150.03     .05       0  336.61      .1       0
   384.2    .045       0   404.1      .1       0
#XS Ineff= 2 , 0
          373.88 1418.68
Permanent Ineff=
       F       F
Bank Sta=384.2,404.1
XS Rating Curve= 0 ,0
Exp/Cntr(USF)=0,0
Exp/Cntr=0.5,0.3

Type RM Length L Ch R = 1 ,2437    ,65.7,63.1,63.1
XS GIS Cut Line= 3
2485774.74496248672380.6683661662486007.31543371672565.358400561
2486073.16306306 672604.09230018
#Sta/Elev= 30
       0 1421.23    25.5 1418.28    35.7 1417.53    41.4 1417.44    56.2 1416.72
    61.4 1416.78   102.2 1416.06   119.4 1415.34   132.5 1415.19   164.4 1413.51
   199.2 1412.44   229.3 1411.85   240.7 1411.02   243.6 1410.62   250.3 1409.04
   254.4 1408.47   263.5 1407.76   275.8  1407.9   280.9 1408.34   286.3 1409.91
   291.1 1412.69   296.3 1415.08   300.6 1416.25   305.6 1416.87   310.2 1416.85
   315.8 1417.15   326.9 1418.26   338.6 1419.92     352 1421.28   373.4 1424.36
#Mann= 9 ,-1 , 0
       0     .06       0   52.97     .05       0      91     .06       0
  200.43      .1       0  223.76     .06       0   254.4    .045       0
   280.9     .06       0  341.53      .1       0  366.06     .06       0
#XS Ineff= 2 , 0
          235.93  1414.7  288.87            1415
Permanent Ineff=
       F       F
Bank Sta=254.4,280.9
XS Rating Curve= 0 ,0
Exp/Cntr(USF)=0,0
Exp/Cntr=0.5,0.3

Type RM Length L Ch R = 1 ,2374    ,83.1,81.8,79.9
XS GIS Cut Line= 2
2485704.99305086672429.5057063632486094.42222823 672698.07364692
#Sta/Elev= 30
       0 1424.51    11.8 1423.12    28.1 1421.94      41 1420.37    62.6  1418.9
    79.9 1417.16    88.5 1416.52    94.4 1416.59   118.7 1415.39   157.5  1412.5
   181.9 1411.24   192.7 1411.29   258.2 1409.47   274.2 1407.13   279.1 1405.91
   283.9 1403.75     287 1402.86   301.3 1401.62   315.7 1400.69   322.8  1400.9
   327.7 1401.99   332.5 1406.07   337.4 1408.19   368.8 1409.82   375.9 1411.43
   384.7 1414.34   387.6 1414.89   424.2 1419.87   449.2 1423.94   473.1 1425.19
#Mann= 4 ,-1 , 0
       0     .05       0   18.05     .06       0   301.3    .045       0
   327.7     .06       0
Bank Sta=301.3,327.7
XS Rating Curve= 0 ,0
Exp/Cntr(USF)=0,0
Exp/Cntr=0.5,0.3

Type RM Length L Ch R = 1 ,2293    ,306.2,307.7,308.4
XS GIS Cut Line= 3
2485618.33968746672507.9699281372486023.27244833672732.636569589
2486123.61762811672710.436308576
#Sta/Elev= 30
       0 1426.66      39 1423.26    73.7 1416.82     124 1412.08   151.4 1411.49
   238.3 1407.24   261.2 1407.03   279.5 1408.23   293.2 1408.16   297.8 1407.65
   306.9 1405.23   323.1 1404.31   326.1 1403.52   332.6 1400.11     339 1397.62
   343.5 1397.24   352.7 1400.31   361.8  1403.7   375.6 1406.37   398.4 1404.84
   417.3 1405.79   426.5 1408.24   434.9 1409.12   449.6    1409   463.1  1409.9
   487.6 1409.18   504.4 1414.09   527.8 1423.01   556.8 1425.68   565.9 1424.65
#Mann= 7 ,-1 , 0
       0     .05       0   15.03      .1       0   332.6    .045       0
   352.7      .1       0  394.32     .06       0  419.95      .1       0
  508.46     .06       0
Bank Sta=332.6,352.7
XS Rating Curve= 0 ,0
Exp/Cntr(USF)=0,0
Exp/Cntr=0.3,0.1

Type RM Length L Ch R = 1 ,1985    ,152.6,156.7,161.3
XS GIS Cut Line= 3
2485453.67213631 672616.609159652485557.46819726672780.295607628
2485833.04005479672965.496988875
#Sta/Elev= 30
       0 1428.65    31.1 1424.42    54.8 1418.98      88 1412.65   154.3 1406.07
   168.5 1403.79   238.7 1395.25   253.2 1394.98   274.4 1395.62   314.8 1395.25
   326.3 1395.65   340.7 1395.51   366.7  1394.1   375.3  1393.3   381.1 1392.23
   388.1  1390.6   397.8 1390.22   401.3 1391.11   404.1 1392.33   407.4 1393.68
   418.6 1394.11   421.9 1394.66   427.9 1397.75   447.4 1406.34   460.4 1413.03
   467.5 1415.42   476.2  1416.9   492.5 1418.88   508.6 1419.87   525.8 1420.34
#Mann= 5 ,-1 , 0
       0     .05       0  191.55      .1       0     352      .1       0
   381.1    .045       0   404.1      .1       0
#XS Ineff= 2 , 0
          344.96 1398.23
Permanent Ineff=
       F       F
Bank Sta=381.1,404.1
XS Rating Curve= 0 ,0
Exp/Cntr(USF)=0,0
Exp/Cntr=0.3,0.1

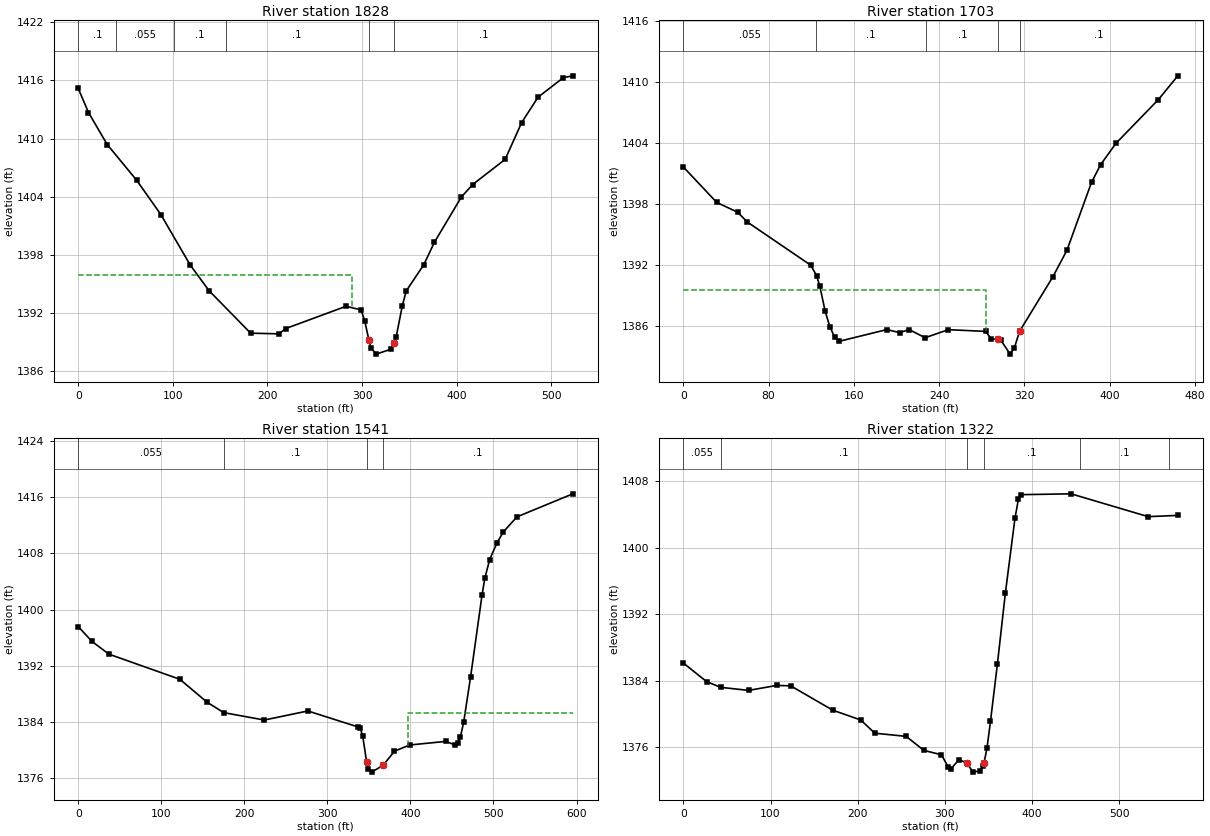
Type RM Length L Ch R = 1 ,1828    ,142.6,125.3,95.7
XS GIS Cut Line= 4
2485416.96307805672765.4793655492485713.31362113673105.740587609
2485725.19421076673104.7115066942485784.74737277673103.442862002
#Sta/Elev= 30
       0 1415.16    10.8 1412.68    30.6 1409.38    61.8 1405.69    87.3 1402.16
   118.4 1396.95   138.4  1394.3   182.2 1389.94   212.1 1389.87   219.4 1390.42
     283 1392.71   298.9 1392.34   302.8  1391.2   307.2 1389.23   309.5 1388.42
   314.8 1387.78   330.7 1388.29     334 1388.97   336.1 1389.59   342.5 1392.76
   346.7  1394.3   365.2 1396.99   376.5 1399.32     405 1403.98   416.9 1405.26
   451.2 1407.85   468.7 1411.65     486 1414.26   512.7 1416.27   522.7 1416.46
#Mann= 6 ,-1 , 0
       0      .1       0   40.33    .055       0  100.76      .1       0
  155.63      .1       0   307.2    .045       0     334      .1       0
#XS Ineff= 2 , 0
          289.75 1395.98
Permanent Ineff=
       F       F
Bank Sta=307.2,334
XS Rating Curve= 0 ,0
Exp/Cntr(USF)=0,0
Exp/Cntr=0.3,0.1

Type RM Length L Ch R = 1 ,1703    ,162.1,162.2,162.3
XS GIS Cut Line= 5
2485330.44427823673135.516497075 2485430.6826023673192.121668314
2485648.84836645673085.9869722422485672.29231567673076.959692878
2485733.05877423673130.447950333
#Sta/Elev= 30
       0 1401.64    31.3 1398.16    50.9  1397.2    60.1 1396.23   119.6 1391.99
   125.1 1390.95   128.1 1389.91     133  1387.5   137.4 1385.98   141.9 1384.93
   146.3 1384.53   190.9 1385.68   202.9 1385.38   211.8 1385.68   226.8 1384.88
   248.6 1385.67   283.7  1385.5   288.7 1384.77   295.6 1384.71   297.6 1384.67
   306.5 1383.27   310.6 1383.92   315.4 1385.51   346.5 1390.84   359.8 1393.46
   382.9 1400.14   391.4 1401.86   405.8 1403.96   445.5 1408.24   463.8 1410.58
#Mann= 5 ,-1 , 0
       0    .055       0  124.08      .1       0  227.78      .1       0
   295.6    .045       0   315.4      .1       0
#XS Ineff= 2 , 0
          283.52 1389.53
Permanent Ineff=
       F       F
Bank Sta=295.6,315.4
XS Rating Curve= 0 ,0
Exp/Cntr(USF)=0,0
Exp/Cntr=0.3,0.1

Type RM Length L Ch R = 1 ,1541    ,210.5,219,227.2
XS GIS Cut Line= 3
2485282.40491267673259.6357412742485531.28921689673305.334836684
2485830.09099457673138.005841185
#Sta/Elev= 30
       0 1397.59    16.6 1395.48    36.9 1393.68   122.4  1390.1   154.9 1386.86
   175.2 1385.36     224 1384.31   276.5  1385.6   336.7 1383.33   339.7 1383.14
   342.6 1381.97   347.21378.381   348.7 1377.39   353.3  1376.9     367 1377.86
   380.8 1379.88   399.1 1380.76   442.5 1381.27   454.1 1380.75   457.2 1381.08
   460.2 1381.93   464.1    1384   472.5  1390.5   486.2 1402.07   489.5 1404.44
   495.4 1407.13   504.2  1409.5   511.8 1411.05   528.2  1413.2   595.5 1416.48
#Mann= 4 ,-1 , 0
       0    .055       0  175.96      .1       0   347.2    .045       0
     367      .1       0
#XS Ineff= 2 , 0
                          396.49         1385.27
Permanent Ineff=
       F       F
Bank Sta=347.2,367
XS Rating Curve= 0 ,0
Exp/Cntr(USF)=0,0
Exp/Cntr=0.3,0.1

Type RM Length L Ch R = 1 ,1322    ,239.8,243,245.5
XS GIS Cut Line= 2
 2485424.1585024673362.7059857842485988.60479618673416.651805686
#Sta/Elev= 30
       0 1386.12    26.7 1383.88    42.8 1383.19    74.9 1382.82   107.1 1383.42
   123.1 1383.37   171.3 1380.44   203.5 1379.25   219.6 1377.66   255.6 1377.28
   275.8 1375.59     296 1375.06     304 1373.53     307 1373.36     316 1374.48
   325.31374.059   332.1 1372.97   340.1 1373.13   344.1  1373.7   344.8 1374.06
   348.2 1375.87   352.2 1379.08   360.2 1386.06   369.3 1394.57   380.3 1403.58
   384.3 1405.92   387.6 1406.41   444.6 1406.51     533 1403.76     567 1403.91
#Mann= 6 ,-1 , 0
       0    .055       0   43.74      .1       0   325.3    .045       0
   344.8      .1       0  454.39      .1       0  557.05      .1       0
Bank Sta=325.3,344.8
XS Rating Curve= 0 ,0
Exp/Cntr=0.3,0.1