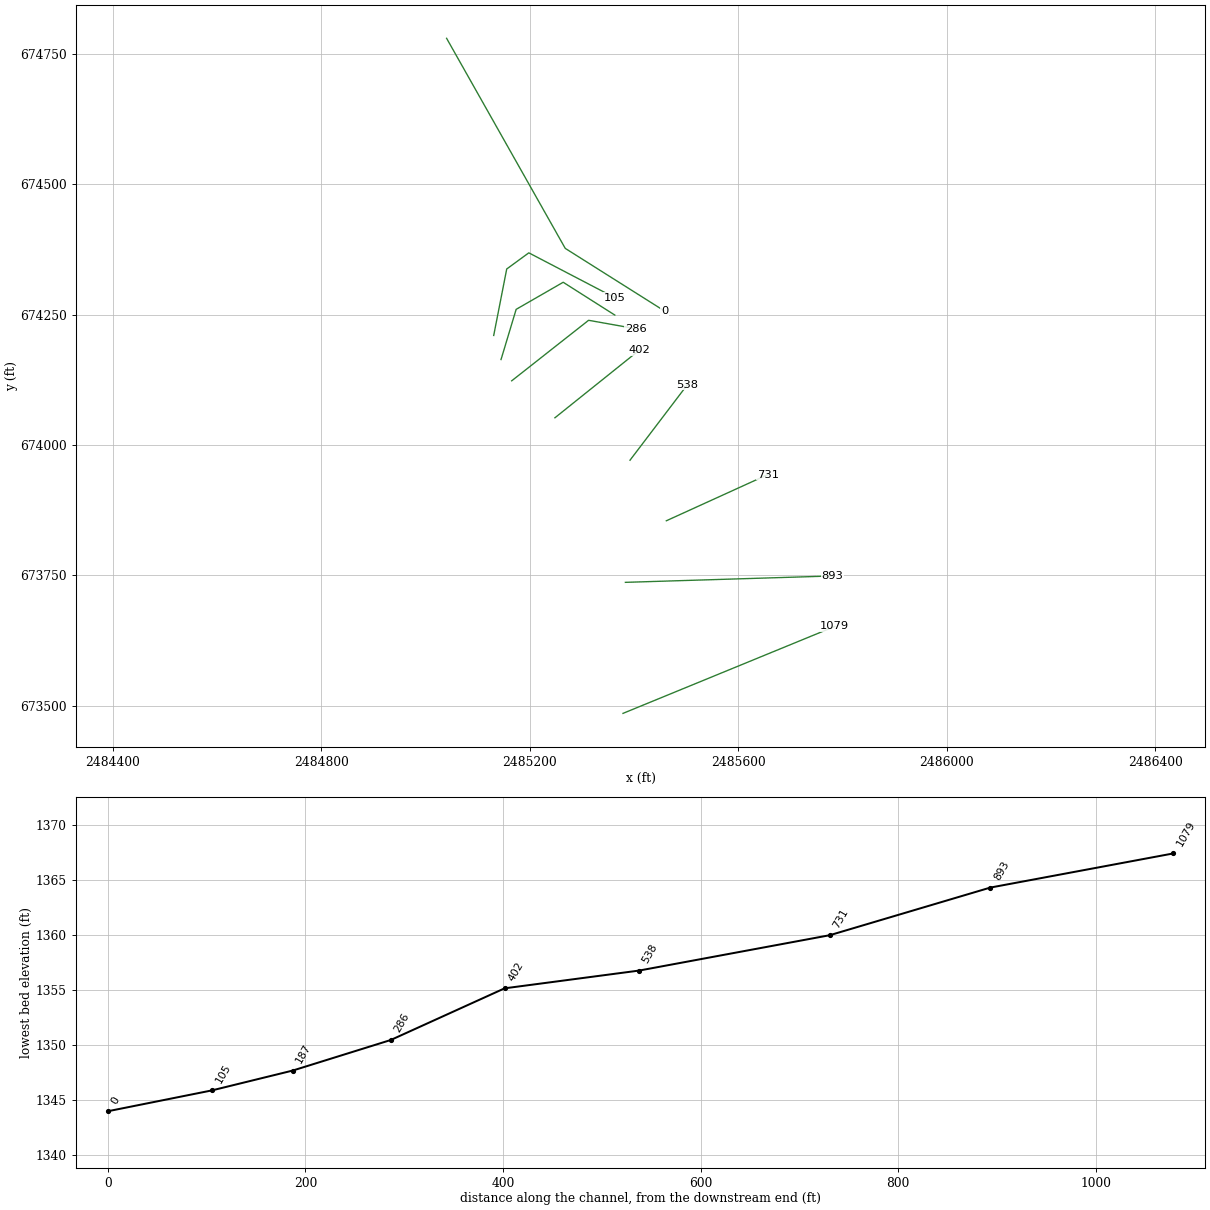
HEC-RAS study KESSNERRN.prj: KESSNERRN

--- KESSNERRN.g01 (geometry) --- (continued)

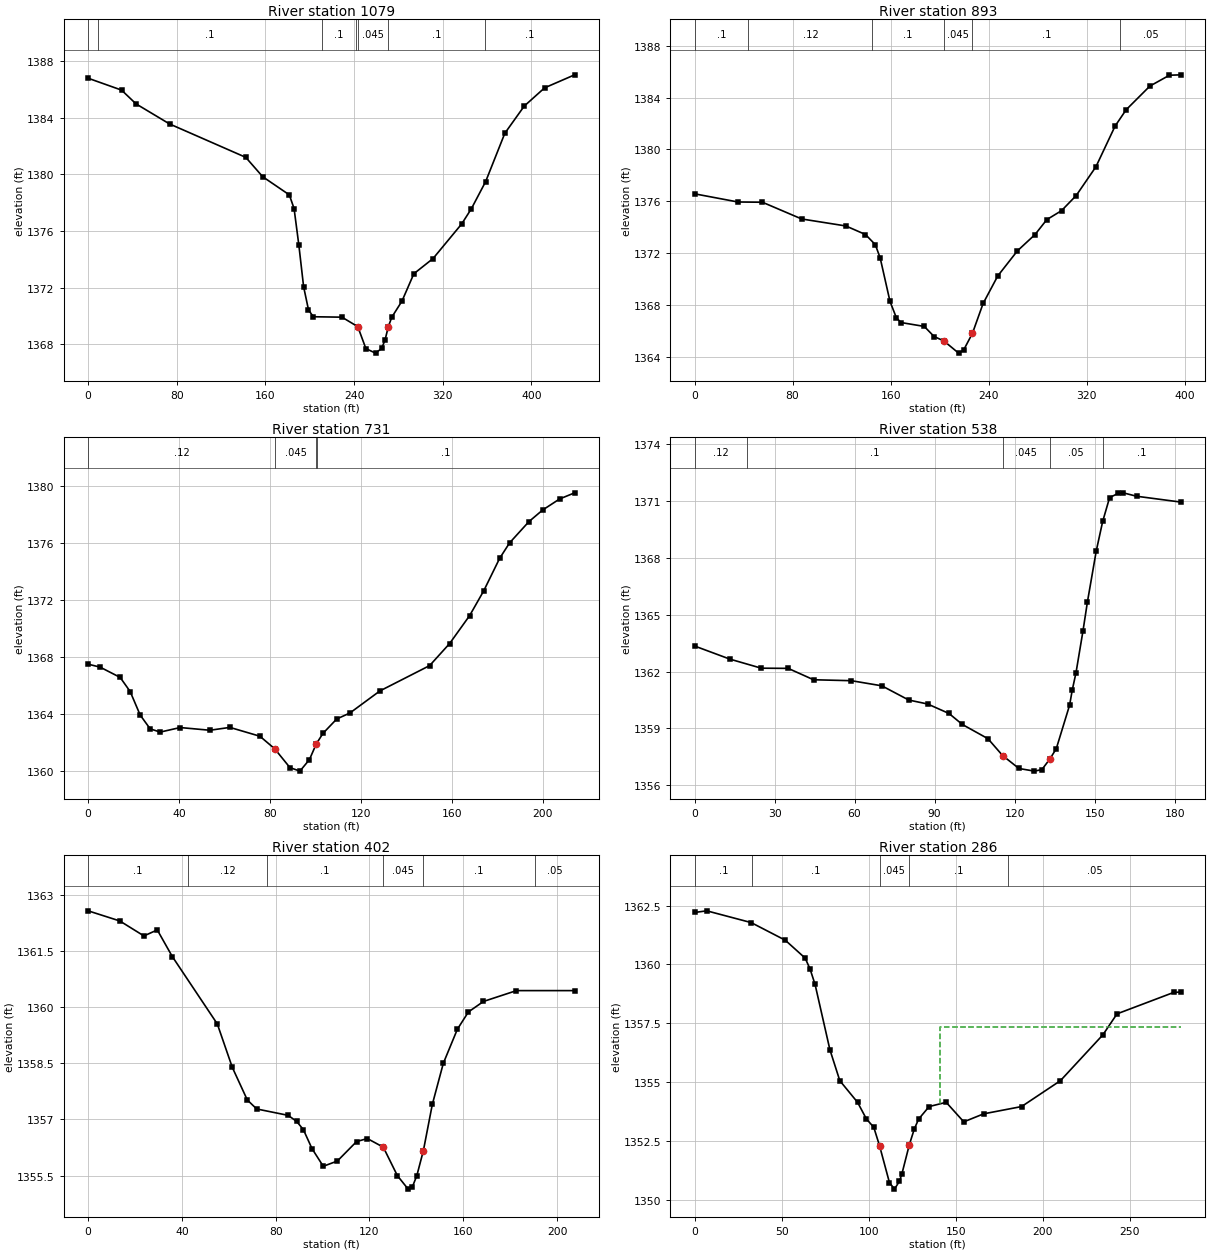
Type RM Length L Ch R = 1 ,1079    ,190.8,185.4,177.9
XS GIS Cut Line= 2
 2485378.7753223673485.2412274992485784.97437437673651.928217993
#Sta/Elev= 30
       0  1386.8    30.2 1385.96    43.2 1384.99    73.5 1383.57   142.3 1381.21
   157.6 1379.84   181.6 1378.56   185.9 1377.59   190.2 1375.01   194.5 1372.07
   198.9 1370.44   203.2 1369.95   229.1 1369.92   243.4 1369.25   250.7  1367.7
   259.4 1367.38   264.9 1367.71     268 1368.31     271 1369.26   274.1 1369.92
   283.3 1371.06     294 1372.99   311.3 1374.06   337.2 1376.51   345.9 1377.58
   358.8  1379.5   376.1 1382.91   393.6 1384.83     412 1386.12   439.1 1387.04
#Mann= 7 ,-1 , 0
       0    .055       0    8.69      .1       0   210.9      .1       0
   241.7      .1       0   243.4    .045       0     271      .1       0
   358.2      .1       0
Bank Sta=243.4,271
XS Rating Curve= 0 ,0
Exp/Cntr=0.3,0.1

Type RM Length L Ch R = 1 ,893     ,155.2,162.5,168.2
XS GIS Cut Line= 2
2485383.34466468673736.6378139732485780.30422928673748.889547584
#Sta/Elev= 30
       0 1376.57    35.4 1375.94    55.4 1375.92    87.4 1374.63   123.5 1374.09
   139.5 1373.43   147.5 1372.65   151.5 1371.62   159.5 1368.27   164.7 1367.01
   168.5 1366.64   187.5 1366.34   195.5 1365.56   203.5 1365.22   215.5 1364.28
   219.5  1364.5   226.8 1365.81   235.5 1368.11   247.5 1370.24   263.5 1372.17
   277.9 1373.43   287.5 1374.58   299.5 1375.27   311.5 1376.44   327.6 1378.66
   343.2 1381.79   352.2 1383.05   371.6 1384.88   387.6 1385.72   397.1 1385.75
#Mann= 6 ,-1 , 0
       0      .1       0   43.94     .12       0   145.1      .1       0
   203.5    .045       0   226.8      .1       0  347.43     .05       0
Bank Sta=203.5,226.8
XS Rating Curve= 0 ,0
Exp/Cntr(USF)=0,0
Exp/Cntr=0.3,0.1

Type RM Length L Ch R = 1 ,731     ,187,193.1,200.4
XS GIS Cut Line= 2
2485461.93067755673854.7680994662485656.76219263673943.468729593
#Sta/Elev= 30
       0 1367.47     5.3 1367.26    14.1 1366.54    18.5 1365.55    22.9  1363.9
    27.3 1362.93    31.7  1362.7    40.5 1363.02    53.6 1362.83    62.4 1363.03
    75.6 1362.41    82.1 1361.53    88.8 1360.21    93.2 1359.96    97.4 1360.77
   100.4 1361.87   103.4 1362.62   109.4 1363.62   115.2 1364.04   128.4 1365.59
   150.3 1367.37   159.1 1368.92   167.9 1370.88   174.1 1372.62   181.1  1374.9
   185.5 1375.99     194 1377.48     200 1378.29   207.5 1379.07   214.1  1379.5
#Mann= 4 ,-1 , 0
       0     .12       0    82.1    .045       0   100.4     .12       0
  100.68      .1       0
Bank Sta=82.1,100.4
XS Rating Curve= 0 ,0
Exp/Cntr(USF)=0,0
Exp/Cntr=0.3,0.1

Type RM Length L Ch R = 1 ,538     ,139.8,136.1,132.9
XS GIS Cut Line= 2
2485392.20965824673970.9697983222485502.60127215674116.221921892
#Sta/Elev= 30
       0 1363.35    13.2 1362.66      25 1362.18    35.1 1362.17    44.6 1361.57
    58.8 1361.52    70.2 1361.25    80.3  1360.5    87.4 1360.29    95.4 1359.79
   100.4 1359.21     110 1358.46   115.5 1357.57   121.6 1356.89   127.4 1356.75
   130.2 1356.83   133.1 1357.37   135.6 1357.93   140.6 1360.23   141.6 1361.03
     143 1361.94   145.6 1364.13   147.3 1365.69   150.6 1368.37     153 1369.92
   155.6 1371.18   158.8  1371.4   160.7 1371.43   165.7 1371.25   182.4 1370.94
#Mann= 5 ,-1 , 0
       0     .12       0   19.52      .1       0   115.5    .045       0
   133.1     .05       0  152.98      .1       0
Bank Sta=115.5,133.1
XS Rating Curve= 0 ,0
Exp/Cntr(USF)=0,0
Exp/Cntr=0.3,0.1

Type RM Length L Ch R = 1 ,402     ,114.6,115.3,114.4
XS GIS Cut Line= 2
2485248.20283388674052.4141324082485410.13837824674182.188262033
#Sta/Elev= 30
       0 1362.57    13.5  1362.3    23.8  1361.9    29.5 1362.06    35.9 1361.35
    55.1 1359.55    61.5 1358.39    67.9 1357.52    71.9 1357.28    85.3 1357.11
    88.9 1356.95    91.8 1356.73    95.5 1356.22   100.3 1355.75   106.3 1355.89
   114.5 1356.41   119.1 1356.49   125.9 1356.26   131.9  1355.5   136.5 1355.14
   138.3  1355.2   140.2  1355.5     143 1356.17   146.8  1357.4   151.5  1358.5
   157.5 1359.41   162.2 1359.87   168.6 1360.15   182.7 1360.44   207.5 1360.44
#Mann= 6 ,-1 , 0
       0      .1       0   42.43     .12       0   76.36      .1       0
   125.9    .045       0     143      .1       0  190.61     .05       0
Bank Sta=125.9,143
XS Rating Curve= 0 ,0
Exp/Cntr(USF)=0,0
Exp/Cntr=0.3,0.1

Type RM Length L Ch R = 1 ,286     ,100.9,99.2,96.9
XS GIS Cut Line= 3
2485165.20991804674123.2747350222485312.76263963674239.419044321
2485402.92293506674223.347456276
#Sta/Elev= 30
       0 1362.21       7 1362.28    32.5 1361.78    52.1 1361.03    63.5 1360.27
    66.3 1359.81    69.2 1359.15    77.7 1356.38    83.4 1355.06    93.6 1354.14
    98.7 1353.43   102.9 1353.08   106.2  1352.3   111.9 1350.73   114.8 1350.45
   117.6 1350.78     119 1351.08   123.3 1352.33   126.2 1353.01   128.7 1353.43
   134.7 1353.96   144.5 1354.14   154.6 1353.31     166 1353.65   187.8 1353.96
   210.1 1355.06   234.5 1357.01   242.6  1357.9   275.1 1358.81   279.4 1358.83
#Mann= 5 ,-1 , 0
       0      .1       0   33.08      .1       0   106.2    .045       0
   123.3      .1       0  179.85     .05       0
#XS Ineff= 2 , 0
                          141.19         1357.33
Permanent Ineff=
       F       F
Bank Sta=106.2,123.3
XS Rating Curve= 0 ,0
Exp/Cntr(USF)=0,0
Exp/Cntr=0.3,0.1

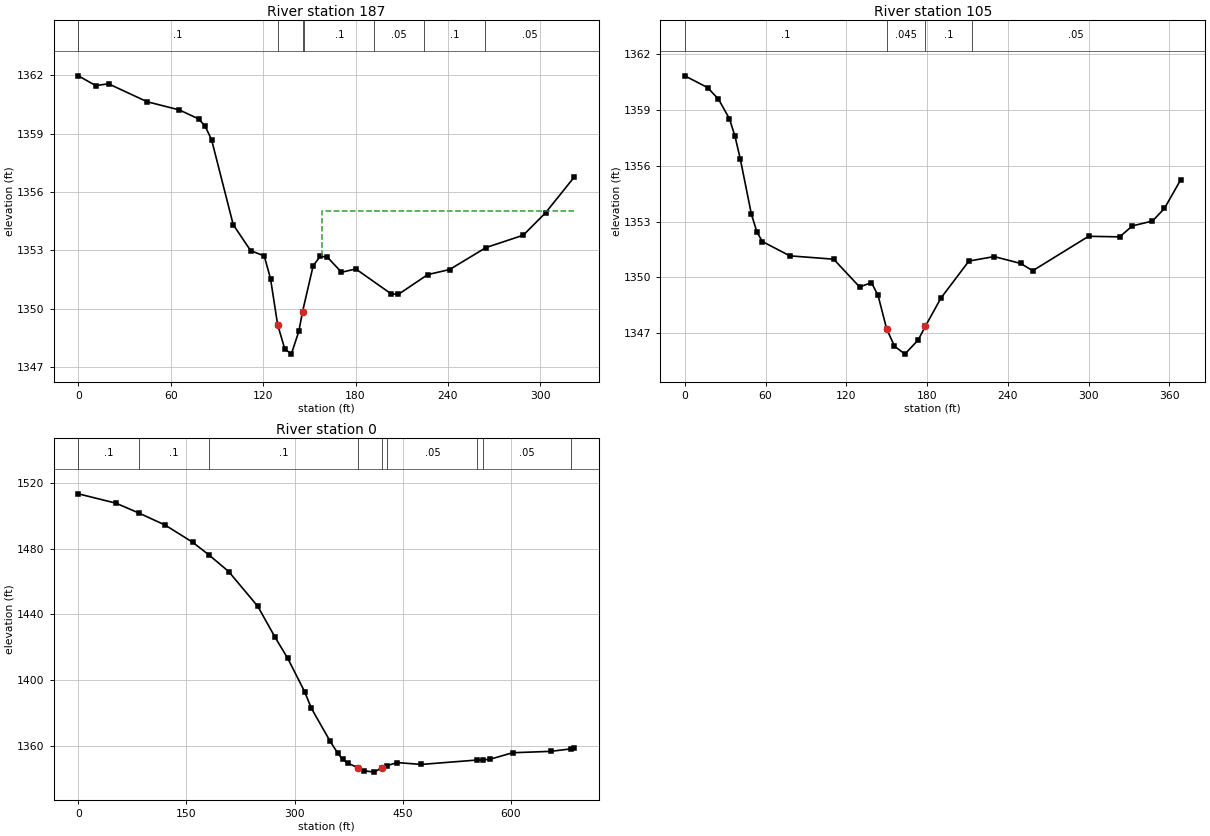
Type RM Length L Ch R = 1 ,187     ,79.6,81.8,85.7
XS GIS Cut Line= 4
2485144.75892602674164.1058001372485173.75540318674260.395988439
2485264.02745471674312.3708059882485363.05315972674249.453921586
#Sta/Elev= 30
       0 1361.96    11.3 1361.46    19.6 1361.55    44.7 1360.63    65.6 1360.21
    78.1 1359.75    82.3 1359.38    86.5 1358.69   100.6 1354.32   111.9 1352.99
   120.7 1352.72   124.8 1351.56   129.4  1349.2     134 1347.96   138.3 1347.68
   143.2 1348.85   145.6 1349.86   152.5 1352.21   157.1  1352.7   161.7 1352.66
   170.9 1351.88   180.2 1352.05   203.2 1350.77   207.9 1350.75   226.9 1351.76
   241.1 1352.02   264.8 1353.15   288.9 1353.78   303.4 1354.93     322 1356.76
#Mann= 7 ,-1 , 0
       0      .1       0   129.4    .045       0   145.6      .1       0
  146.84      .1       0  192.11     .05       0  224.45      .1       0
  263.94     .05       0
#XS Ineff= 2 , 0
                          157.98         1355.03
Permanent Ineff=
       F       F
Bank Sta=129.4,145.6
XS Rating Curve= 0 ,0
Exp/Cntr(USF)=0,0
Exp/Cntr=0.3,0.1

Type RM Length L Ch R = 1 ,105     ,105.3,105.3,105.3
XS GIS Cut Line= 4
2485130.71607438674210.3338786432485155.67103458674337.837841794
2485198.06138995674368.8445533492485362.91456914674282.872734089
#Sta/Elev= 30
       0 1360.83    16.9  1360.2      25 1359.58    33.2 1358.52    37.3 1357.58
    41.3 1356.34    49.5 1353.39    53.6 1352.44    57.6 1351.93      78 1351.16
   110.6 1350.98   129.9 1349.49   138.7 1349.72   143.6 1349.03     150 1347.23
   155.8 1346.31   163.5 1345.88   173.4 1346.64   178.7 1347.37   190.3 1348.89
   211.1 1350.88   229.9 1351.12   249.6 1350.75   258.5 1350.36     300 1352.21
   323.1 1352.18   332.6 1352.77   347.5 1353.03   356.4 1353.71   368.4 1355.24
#Mann= 4 ,-1 , 0
       0      .1       0     150    .045       0   178.7      .1       0
  213.26     .05       0
Bank Sta=150,178.7
XS Rating Curve= 0 ,0
Exp/Cntr(USF)=0,0
Exp/Cntr=0.3,0.1

Type RM Length L Ch R = 1 ,0       ,,,
XS GIS Cut Line= 3
     2485040.359      674780.3952485267.97494219674377.391061374
2485458.26435143674257.326527521
#Sta/Elev= 30
       0 1513.31    52.3 1507.61    84.4 1501.54   120.3 1494.33   158.5 1483.87
   180.9 1476.25   208.5 1466.05   248.9  1444.9   272.9 1426.06   290.6 1413.14
   313.9 1392.97   323.3 1382.84   349.3 1362.76   360.1 1355.34   366.9  1351.7
   373.8 1349.44   388.2 1346.64   396.2 1344.82   410.6 1343.99   420.81346.714
   428.5 1348.01   442.7 1349.79   475.6 1348.67   553.7 1351.37   560.7 1351.42
   571.1 1351.82   602.5 1355.79   655.3 1356.63   683.7 1358.16 687.842  1358.4
#Mann= 9 ,-1 , 0
       0      .1       0    84.4      .1       0   180.9      .1       0
   388.2    .045       0   420.8      .1       0   428.5     .05       0
   553.7      .1       0   560.7     .05       0   683.7      .1       0
Bank Sta=388.2,420.8
XS Rating Curve= 0 ,0
Exp/Cntr(USF)=0,0
Exp/Cntr=0.3,0.1
LCMann Table=0

Chan Stop Cuts=-1
Use User Specified Reach Order=0
Composite Channel Slope=5